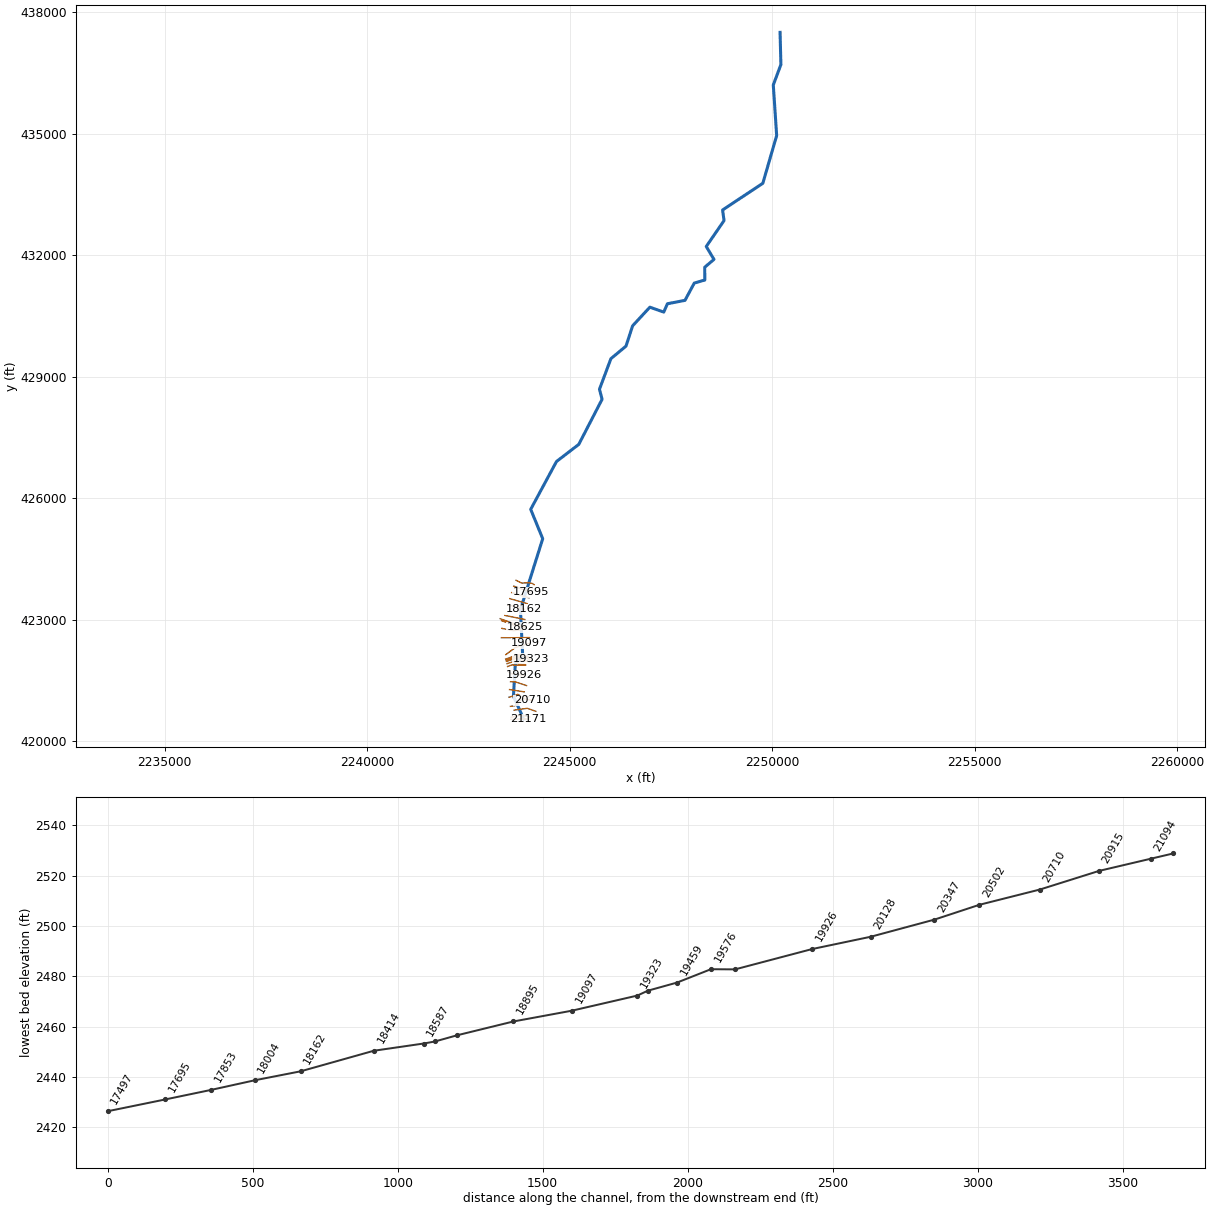
--- CMMNGSCK.prj (project) ---

Proj Title=CMMNGSCK
Current Plan=p01
Default Exp/Contr=0,0
English Units
Geom File=g01
Flow File=f01
Plan File=p01
Background Map Layer=FWY
BEGIN DESCRIPTION:
----------MODEL BY WOOD PLC 2021----------
Stream Name: Cummings Creek
Flood Zone: Enhanced Approximate / Detailed
Pocahontas County, WV
HEC-RAS Version: RAS 6.1
Vertical Datum: NAVD88
Projection: NAD 1983 StatePlane West Virginia S FIPS 4702 (US Feet)
Terrain: 1-meter LIDAR (FEMA Region III 3DEP collected 2016-2018)
Land Use: 2016 NLCD
Hydrologic Method:
WV SIR2010-5033 regression equations
Model Notes:
Detailed study - Zone AE with floodway - from the confluence to XS 15134
XS 15134 to upstream is all Zone A
END DESCRIPTION:
DSS Export Rating Curves= 0
DSS Export Rating Curve Sorted= 0
DSS Export Volume Flow Curves= 0
DXF OffsetX= 0
DXF OffsetY= 0
DXF ScaleX= 0
DXF ScaleY= 0

--- CMMNGSCK.p01 (plan) ---

Plan Title=Floodplain
Program Version=6.10
Short Identifier=Floodplain
Geom File=g01
Flow File=f01
Subcritical Flow
K Sum by GR= 0
Std Step Tol= 0.01
Critical Tol= 0.01
Num of Std Step Trials= 20
Max Error Tol= 0.3
Flow Tol Ratio= 0.001
Split Flow NTrial= 30
Split Flow Tol= 0.02
Split Flow Ratio= 0.02
Log Output Level= 0
Friction Slope Method= 1
Unsteady Friction Slope Method= 2
Unsteady Bridges Friction Slope Method= 1
Parabolic Critical Depth
Global Vel Dist= 0 , 0 , 0
Global Log Level= 0
CheckData=True
Encroach Param=-1 ,5,5, 2
Encroach River=CMMNGSCK
Encroach Reach=Main
Encroach Node=15134
       1     396     442
Encroach Node=14902
       1   410.8     445
Encroach Node=14708
       1     482   519.5
Encroach Node=14474
       1     440   479.2
Encroach Node=14158
       1     446     474
Encroach Node=13830
       1   506.2   531.7
Encroach Node=13586
       1     533  589.96
Encroach Node=13189
       1     515   583.6
Encroach Node=12885
       1   443.8     500
Encroach Node=12523
       1     440     484
Encroach Node=12175
       1     429     474
Encroach Node=11692
       1     183     260
Encroach Node=11379
       1     192     242
Encroach Node=10885
       1    44.8   85.58
Encroach Node=10600
       1    71.8   112.6
Encroach Node=10266
       1   165.5   216.7
Encroach Node=9777
       1    41.8     210
Encroach Node=9321
       1   211.9     340
Encroach Node=8930
       1     500     630
Encroach Node=8896
       1     504   619.5
Encroach Node=8573
       1     500     575
Encroach Node=8001
       1  616.64     746
Encroach Node=7637
       1     490     656
Encroach Node=7043
       1     506   635.9
Encroach Node=6729
       1     570   696.2
Encroach Node=6183
       1     221     302
Encroach Node=5915
       1  247.58   316.6
Encroach Node=5647
       1   225.8     293
Encroach Node=5420
       1  350.27   411.2
Encroach Node=5077
       1     161     215
Encroach Node=4829
       1     115     158
Encroach Node=4624
       1   155.7   205.8
Encroach Node=4235
       1     408   464.2
Encroach Node=3853
       1     685     750
Encroach Node=3791
       1   719.8   768.8
Encroach Node=3590
       1     722     768
Encroach Node=3350
       1     768     815
Encroach Node=2867
       1     752     810
Encroach Node=2381
       1   658.5     725
Encroach Node=2086
       1     953    1055
Encroach Node=1942
       1     914  988.56
Encroach Node=1472
       1     637     833
Encroach Node=1163
       1  669.98  841.27
Encroach Node=746
       1  788.84  1034.2
Encroach Node=142
       1 1200.13 1374.63
Mapping Interval=1HOUR
Computation Time Step Use Courant=        0
Computation Time Step Use Time Series=    0
Computation Time Step Count To Double=0
Computation Time Step Max Doubling=0
Computation Time Step Max Halving=0
Computation Time Step Residence Courant=0
Run HTab= 0
Run UNet= 0
Run Sediment= 0
Run PostProcess= 0
Run WQNet= 0
Run RASMapper=-1
UNET Theta= 0
UNET Theta Warmup= 0
UNET ZTol= 0
UNET ZSATol= 0
UNET MxIter= 0
UNET Max Iter WO Improvement= 0
UNET MaxInSteps= 0
UNET DtIC= 0
UNET DtMin= 0
UNET MaxCRTS= 0
UNET WFStab= 0
UNET SFStab= 0
UNET WFX= 1
UNET SFX= 1
UNET Gravity=32.174
UNET 1D Methodology=Finite Difference
UNET DSS MLevel= 1
UNET Pardiso=0
UNET DZMax Abort= 0
UNET Use Existing IB Tables= 0
UNET Froude Reduction=False
UNET Froude Limit= 0
UNET Froude Power= 0
UNET D1 Cores= 0
UNET WindReference=Eulerian
UNET WindDragFormulation=Hsu (1988)
UNET D2 Coriolis=0
UNET D2 Cores= 0
UNET D2 Theta= 1
UNET D2 Theta Warmup= 1
UNET D2 Z Tol= 0.01
UNET D2 Volume Tol= 0.01
UNET D2 Max Iterations= 20
UNET D2 Equation= 0
UNET D2 RampUpFraction=0.1
UNET D2 TimeSlices= 1
UNET D2 Turbulence Formulation=Non-Conservative (original)
UNET D2 Eddy Viscosity=0.3
UNET D2 Transverse Eddy Viscosity=0.1
UNET D2 Smagorinsky Mixing=0
UNET D2 BCVolumeCheck=0
UNET D2 Cores=0
UNET D2 SolverType=PARDISO (Direct)
UNET D2 Minimum Iterations= 2147483647
UNET D2 Maximum Iterations= 2147483647
UNET D2 Restart Number= 10
UNET D2 Relaxation Coeff=1.3
UNET D2 SOR Precondition Iterations= 10
UNET D2 ILUT Maximum Fill= 8
UNET D2 ILUT Tolerance=1E-08
UNET D1D2 MaxIter= 0
UNET D1D2 ZTol=0.01
UNET D1D2 QTol=0.1
UNET D1D2 MinQTol=1
Write IC File= 0
Write IC File at Fixed DateTime=0
Write IC File at Sim End=0
Echo Input=False
Echo Parameters=False
Echo Output=False
Write Detailed= 0
HDF Write Warmup=0
HDF Write Time Slices=0
HDF Flush=0
HDF Compression= 1
HDF Chunk Size= 1
HDF Spatial Parts= 1
HDF Use Max Rows=0
HDF Fixed Rows= 1
Calibration Method= 0
Calibration Iterations= 20
Calibration Max Change=0.05
Calibration Tolerance=0.2
Calibration Maximum=1.5
Calibration Minimum=0.5
Calibration Optimization Method= 1
WQ AD Non Conservative
WQ ULTIMATE=-1
WQ Max Comp Step=1HOUR
WQ Output Interval=15MIN
WQ Output Selected Increments= 0
WQ Output face flow=0
WQ Output face velocity=0
WQ Output face area=0
WQ Output face dispersion=0
WQ Output cell volume=0
WQ Output cell surface area=0
WQ Output cell continuity=0
WQ Output cumulative cell continuity=0
WQ Output face conc=0
WQ Output face dconc_dx=0
WQ Output face courant=0
WQ Output face peclet=0
WQ Output face adv mass=0
WQ Output face disp mass=0
WQ Output cell mass=0
WQ Output cell source sink temp=0
WQ Output nsm pathways=0
WQ Output nsm derived pathways=0
WQ Create Restart=0
WQ Fixed Restart=0
WQ System Summary=0
WQ Write To DSS=0
Sorting and Armoring Iterations= 10
XS Update Threshold= 0.02
Bed Roughness Predictor= 0
Hydraulics Update Threshold= 0.02
Energy Slope Method= 1
Volume Change Method= 1
Sediment Retention Method= 0
Sediment TS Multiplier= 1
Warm Up Method= 0
XS Weighting Method= 0
Number of US Weighted Cross Sections= 1
Number of DS Weighted Cross Sections= 1
Upstream XS Weight=0
Main XS Weight=1
Downstream XS Weight=0
Number of DS XS's Weighted with US Boundary= 1
Upstream Boundary Weight= 1
Weight of XSs Associated with US Boundary= 0
Number of US XS's Weighted with DS Boundary= 1
Downstream Boundary Weight= 0.5
Weight of XSs Associated with DS Boundary= 0.5
Percentile Method= 0
Sediment Output Level= 3
Mass or Volume Output= 0
Output Increment Type= 1
Profile and TS Output Increment= 1
Transport Output Increment 1
XS Output Flag= 0
XS Output Increment= 10
Read HDF5 Sediment Hotstart= 0
Sediment Hotstart Type= 0
Write Gradation File= 0
Read Gradation Hotstart= 0
Write HDF5 File= 1
Write Binary Output= 1
Write DSS Sediment File= 0
DSS Sediment Output Type= 1
SV Curve= 0
Specific Gage Flag= 0
Subcell Erosion Methods= 0
Subcell Deposition Methods= 0
Advection Scheme= 1
Matrix Solver= 0
Implicit Weighting Factor= 1
Maximum Outer Loop Convergence Iterations= 5
Convergence Maximum Absolute= 0.001
Convergence RMSE= 0.0001
Grain Fractions Max Abs Error= 0.001
Max Subgrid Regions= 1
Max Subgrid Length Scale= 3.402823E+38
Initial Layer Thickness= 3.402823E+38
Min Layer Thickness= 3.402823E+38
Max Layer Thickness= 3.402823E+38
Number of Layers= 5

--- CMMNGSCK.f01 (steady flow) ---

Flow Title=Flow
Program Version=6.10
Number of Profiles= 7
Profile Names=01pct,FW,10pct,04pct,02pct,0_2pct,01plus
River Rch & RM=CMMNGSCK,Main            ,21171
     679     679     361     479     576     946    1000
River Rch & RM=CMMNGSCK,Main            ,16753
     760     760     406     537     645    1060    1120
River Rch & RM=CMMNGSCK,Main            ,15854
     972     972     524     690     827    1340    1440
River Rch & RM=CMMNGSCK,Main            ,15134
    1080    1080     585     769     920    1490    1600
River Rch & RM=CMMNGSCK,Main            ,13189
    1320    1320     718     940    1120    1810    1950
River Rch & RM=CMMNGSCK,Main            ,9777
    1530    1530     840    1100    1310    2100    2260
River Rch & RM=CMMNGSCK,Main            ,7637
    1700    1700     936    1220    1450    2320    2510
Boundary for River Rch & Prof#=CMMNGSCK,Main            , 1
Up Type= 0
Dn Type= 3
Dn Slope=0.008456
Boundary for River Rch & Prof#=CMMNGSCK,Main            , 2
Up Type= 0
Dn Type= 3
Dn Slope=0.008456
Boundary for River Rch & Prof#=CMMNGSCK,Main            , 3
Up Type= 0
Dn Type= 3
Dn Slope=0.008456
Boundary for River Rch & Prof#=CMMNGSCK,Main            , 4
Up Type= 0
Dn Type= 3
Dn Slope=0.008456
Boundary for River Rch & Prof#=CMMNGSCK,Main            , 5
Up Type= 0
Dn Type= 3
Dn Slope=0.008456
Boundary for River Rch & Prof#=CMMNGSCK,Main            , 6
Up Type= 0
Dn Type= 3
Dn Slope=0.008456
DSS Import GetInterval= 0
DSS Import GetPeak= 0
DSS Import FillOption= 0

--- CMMNGSCK.g01 (geometry) ---

Geom Title=Geometry
Program Version=6.10

River Reach=CMMNGSCK        ,Main
Reach XY= 30
2243866.84720865420547.0654261842243612.36163582421113.193927035
2243660.43627875421929.9005801382243841.04636328422121.226467401
2243784.95400001423248.709000006 2244335.8101638 425001.79838936
 2244038.9274101425727.4724100832244675.73400004426908.334999993
2245226.49564068427331.6785962582245802.00048021428445.356253368
 2245736.9198839428692.7909224042246019.46600001429447.591000021
 2246392.4860643429758.008170441 2246555.4592144430259.237483293
2246982.49699998430719.8690000182247324.69295822 430598.24037303
2247415.36131504430804.5954342452247849.29999523430888.383914024
  2248078.394554431314.7209513862248338.30655435431390.622375149
2248336.69384068431706.3110757882248565.29600321431899.836716027
2248374.18943347432218.3476655862248813.69330511432858.120687589
2248777.88200003433120.0290000142249771.72400001433779.544000015
2250113.24205518 434957.714037152250029.86300412436207.175590098
2250217.76644985 436710.444671082250197.49025244437506.620034331

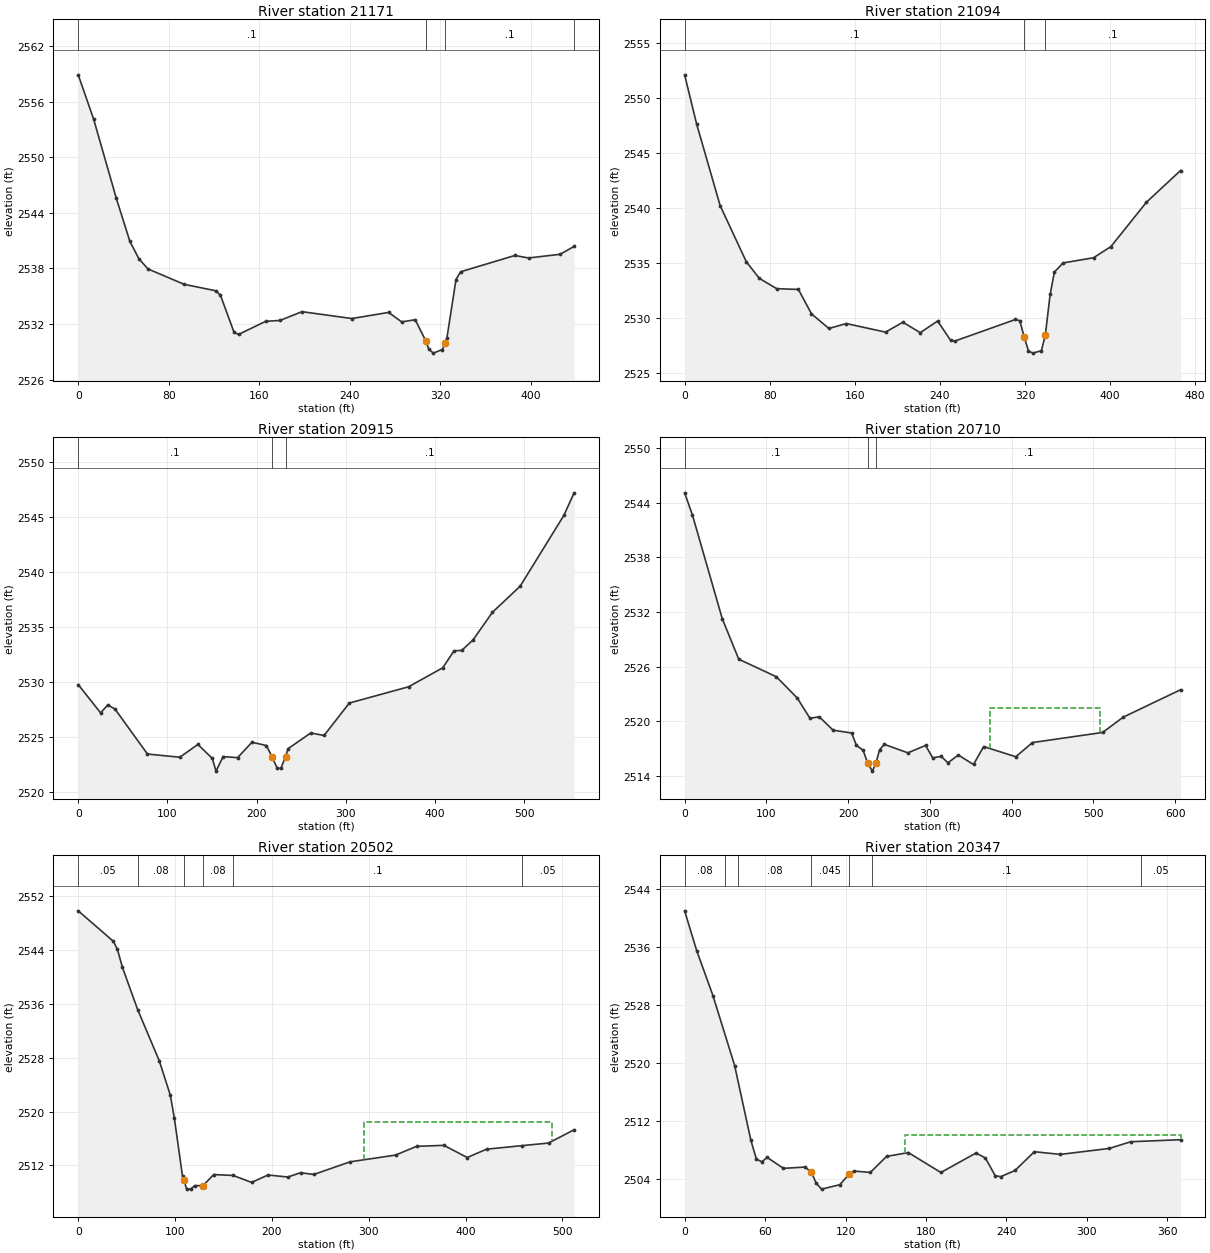
Type RM Length L Ch R = 1 ,21171   ,79.6,76.6,74.3
XS GIS Cut Line= 3
2243550.63588833 420540.991453582243824.86495358420552.771088726
 2243988.4565345  420547.6383845
#Sta/Elev= 30
       0 2558.88    13.6 2554.11    33.6 2545.59    45.6 2540.94    53.6 2539.05
    61.6 2537.95    93.6 2536.29   121.7 2535.59   125.7 2535.11   137.7 2531.11
   141.7 2530.89   165.7  2532.3   178.2 2532.39   197.7 2533.34   241.8  2532.6
   274.2 2533.26   285.8 2532.24   297.8 2532.47   307.2 2530.16   309.8 2529.29
   313.8 2528.87   321.8 2529.26   323.9 2529.91   325.8 2530.52   333.8  2536.8
   337.8 2537.64   385.8  2539.4   397.9 2539.13   425.9 2539.53 438.154 2540.38
#Mann= 4 ,-1,0
       0      .1       0   307.2    .045       0   323.9      .1       0
 438.154      .1       0
Bank Sta=307.2,323.9
XS Rating Curve= 0 ,0
Exp/Cntr(USF)=0,0
Exp/Cntr=0.3,0.1

Type RM Length L Ch R = 1 ,21094   ,175.5,179.6,184.3
XS GIS Cut Line= 4
 2243555.4891293420592.3276532722243790.50749174420642.544209668
2243908.09195011420621.0237657022244011.95867675420597.735903123
#Sta/Elev= 30
       0  2552.1    11.4 2547.59    33.4 2540.21      58 2535.11    70.2  2533.6
    86.6 2532.66     107 2532.59   119.3 2530.37   135.7 2529.04     152 2529.49
   188.9 2528.71   205.2 2529.61   221.6 2528.66   237.9 2529.72   250.2 2527.95
   254.2  2527.9   311.1 2529.86   315.2 2529.74   319.3 2528.26   323.3 2527.01
   327.4  2526.8   335.5 2527.02   339.2 2528.46   343.7 2532.13   347.7 2534.17
   355.9    2535   384.5 2535.47   400.9 2536.49   434.2 2540.51   466.3  2543.4
#Mann= 3 ,-1,0
       0      .1       0   319.3    .045       0   339.2      .1       0
Bank Sta=319.3,339.2
XS Rating Curve= 0 ,0
Exp/Cntr=0.3,0.1

Type RM Length L Ch R = 1 ,20915   ,195.2,204.3,212.3
XS GIS Cut Line= 3
2243627.36802395 420767.370089352243955.31279972420813.962984073
2244166.99439376420739.319670449
#Sta/Elev= 30
       0 2529.78    25.1 2527.21    33.1 2527.93    41.2 2527.56    77.6 2523.48
   113.9 2523.19   134.1 2524.35   150.3 2523.08   154.4 2521.93   162.4 2523.25
   178.6 2523.15   194.7 2524.55   210.9 2524.25   217.4 2523.19     223  2522.2
   227.1 2522.18   232.3 2523.23   235.1 2523.96   260.6 2525.39   275.5 2525.16
   303.8  2528.1   370.3 2529.58   408.5  2531.3   421.2 2532.84   429.7 2532.87
   442.4 2533.82   464.2 2536.33   495.2 2538.69   544.2 2545.11   555.7 2547.16
#Mann= 3 ,-1,0
       0      .1       0   217.4    .045       0   232.3      .1       0
Bank Sta=217.4,232.3
XS Rating Curve= 0 ,0
Exp/Cntr(USF)=0,0
Exp/Cntr=0.3,0.1

Type RM Length L Ch R = 1 ,20710   ,213.2,208.4,205.3
XS GIS Cut Line= 6
2243538.66153504420861.5920387882243649.75389555420877.462376004
2243771.73253279 420995.243528632243845.01113671421056.573119766
2243948.31126676421034.8069080112244069.66344516421010.894813399
#Sta/Elev= 30
       0  2545.1     9.6 2542.65      46 2531.28    66.2 2526.82   112.2 2524.89
   137.8 2522.55   153.3 2520.33   164.7 2520.49   181.6 2519.02   204.3 2518.71
   210.1 2517.36   218.4 2516.81  223.992515.369   229.7 2514.52  234.092515.424
   238.5 2516.87   244.3 2517.46   273.1 2516.53   294.8 2517.34   303.5 2515.97
   313.7 2516.15   322.2 2515.43   334.7 2516.29   353.4 2515.25   365.8 2517.22
   405.1  2516.1   425.5 2517.66   511.3 2518.77   536.5 2520.45   606.6 2523.46
#Mann= 3 ,-1,0
       0      .1       0  223.99    .045       0  234.09      .1       0
#XS Ineff= 1 ,-1
  374.06   508.5 2521.43
Permanent Ineff=
       F
Bank Sta=223.99,234.09
XS Rating Curve= 0 ,0
Exp/Cntr(USF)=0,0
Exp/Cntr=0.3,0.1

Type RM Length L Ch R = 1 ,20502   ,160,155.1,135.7
XS GIS Cut Line= 5
2243501.09479999421088.2661182072243543.69714859421099.737524278
2243722.64628624421157.5595297562243815.51075092421100.822677563
 2243986.5577187421102.586048365
#Sta/Elev= 30
       0 2549.84    36.3 2545.31    40.5 2544.11    45.6 2541.46    61.4 2535.15
    83.8 2527.51    95.1 2522.44    99.3 2518.99   107.7 2510.38   109.2 2509.78
   111.9  2508.5   116.1 2508.46   120.3 2508.98  128.892508.977   139.9 2510.63
     160 2510.49   179.1 2509.46     196 2510.56   216.5 2510.26   229.6  2510.9
   243.3 2510.64   280.8 2512.52   327.7 2513.52   349.4 2514.82   377.7 2514.97
   401.7 2513.16   421.7  2514.4   458.5 2514.93   485.7 2515.31   512.1 2517.29
#Mann= 6 ,-1,0
       0     .05       0    61.4     .08       0   109.2    .045       0
  128.89     .08       0     160      .1       0   458.5     .05       0
#XS Ineff= 1 ,-1
  295.62489.24772518.507
Permanent Ineff=
       F
Bank Sta=109.2,128.89
XS Rating Curve= 0 ,0
Exp/Cntr(USF)=0,0
Exp/Cntr=0.3,0.1

Type RM Length L Ch R = 1 ,20347   ,219.9,219.2,213.5
XS GIS Cut Line= 2
2243515.32181888421276.4971266272243880.76155998421219.558894016
#Sta/Elev= 30
       0 2541.03       9 2535.53    21.1 2529.32    37.3 2519.65    49.4 2509.32
    53.5 2506.73    57.5 2506.35    61.6 2506.95    73.7 2505.44    89.9 2505.62
    94.62504.882      98 2503.43   102.1 2502.57   115.7 2503.18   122.62504.607
   126.4 2505.06   138.5 2504.88   150.6 2507.09   166.8 2507.62   191.1 2504.87
   217.3 2507.56   224.3 2506.87   231.6 2504.43   235.7 2504.29   246.4 2505.15
   260.8 2507.74   280.2 2507.37   316.6 2508.19   332.7 2509.12   369.8  2509.4
#Mann= 7 ,-1,0
       0     .08       0      30     .05       0      40     .08       0
    94.6    .045       0   122.6     .08       0     140      .1       0
     340     .05       0
#XS Ineff= 2 , 0
                          164.58         2510.02
Permanent Ineff=
       F       F
Bank Sta=94.6,122.6
XS Rating Curve= 0 ,0
Exp/Cntr(USF)=0,0
Exp/Cntr=0.3,0.1

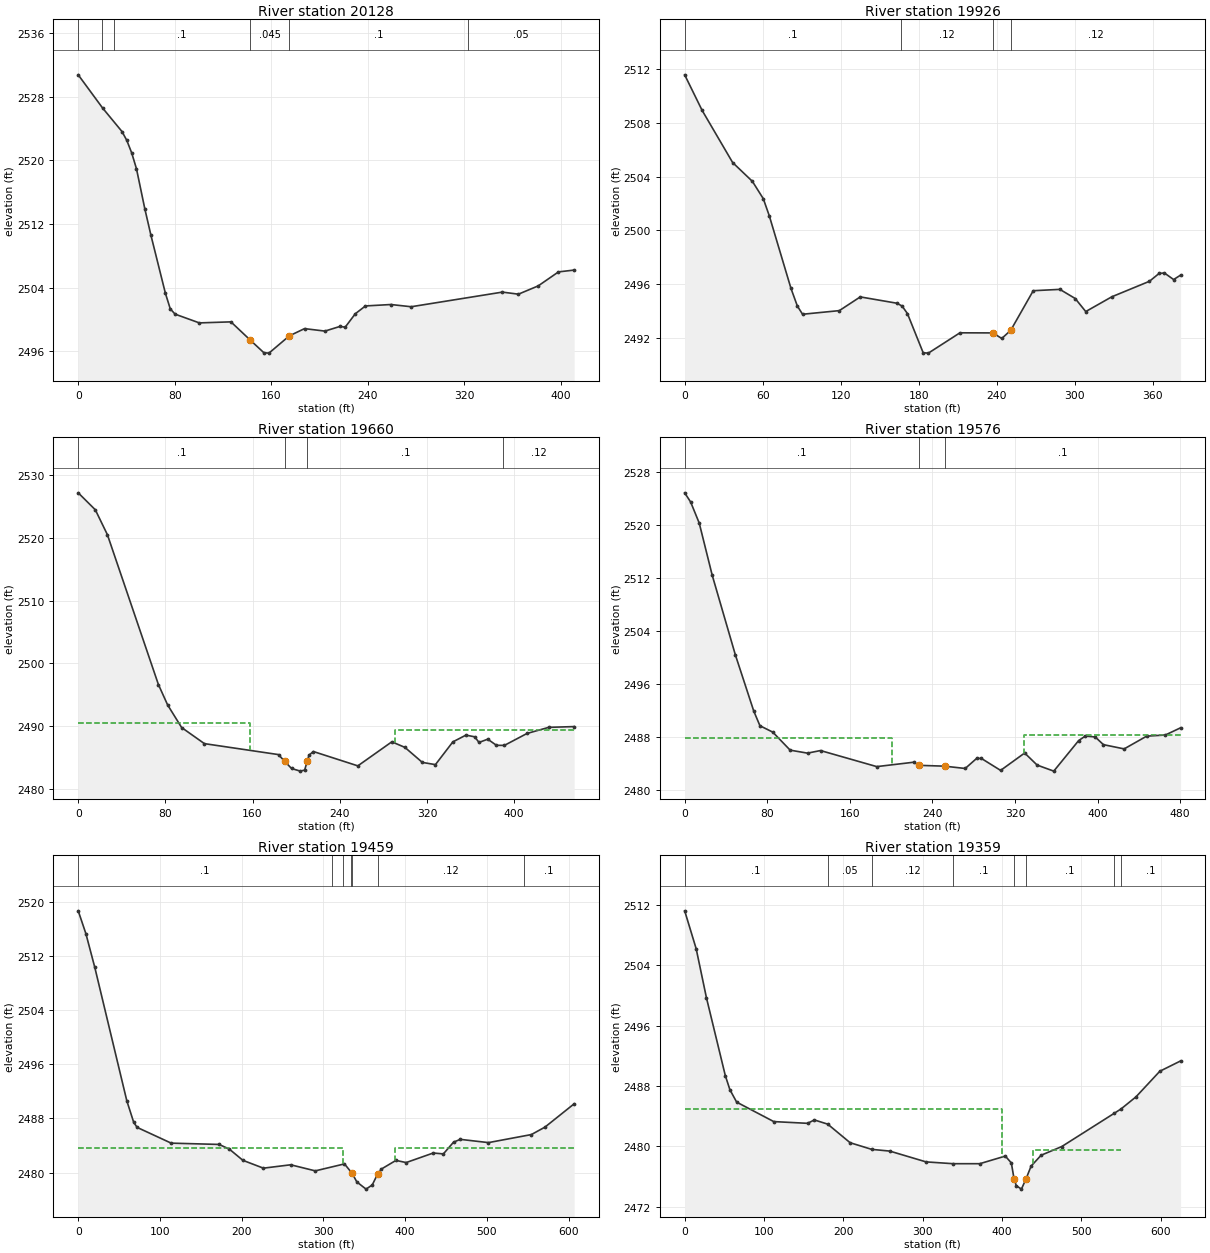
Type RM Length L Ch R = 1 ,20128   ,198.6,202.3,206.1
XS GIS Cut Line= 3
2243539.98384255 421471.341349332243663.16267963421464.188602045
2243936.47216357421374.343860782
#Sta/Elev= 30
       0 2530.75    20.2 2526.58    36.3 2523.62    40.3  2522.5    44.3 2520.95
    48.3 2518.94    55.2 2513.92    60.3 2510.57    72.3 2503.28    76.3 2501.34
    80.3 2500.67   100.4 2499.57   126.6  2499.7   142.4 2497.44   153.9 2495.82
   158.1 2495.77     175 2497.94   187.6 2498.85   204.5 2498.54   217.1 2499.13
   221.3 2499.03   229.7 2500.72   238.1  2501.7   259.2 2501.88     276  2501.6
   351.6 2503.44   364.9 2503.18   381.3 2504.22   398.1 2505.98   411.1 2506.21
#Mann= 6 ,-1,0
       0      .1       0      20     .12       0      30      .1       0
   142.4    .045       0     175      .1       0  323.39     .05       0
Bank Sta=142.4,175
XS Rating Curve= 0 ,0
Exp/Cntr(USF)=0,0
Exp/Cntr=0.3,0.1

Type RM Length L Ch R = 1 ,19926   ,263.7,265.8,267.5
XS GIS Cut Line= 3
2243499.59634293421706.9228776812243566.39333791421668.962038298
2243868.62728443421629.431363855
#Sta/Elev= 30
       0 2511.57    13.4 2508.93    36.9 2505.05    52.1 2503.65    60.5 2502.36
    65.1 2501.09    81.8 2495.69    86.7 2494.38    90.7 2493.77     119 2494.04
   135.1 2495.06   163.3 2494.59   167.3 2494.38   171.4 2493.82   183.5 2490.91
   187.5 2490.88   211.8 2492.39   237.12492.383     244 2491.97   250.9 2492.58
   268.2 2495.52   288.7 2495.62   300.5 2494.94   308.6 2493.97   328.7 2495.07
   357.6 2496.22     365  2496.8   369.1 2496.84   376.2 2496.35   381.6 2496.68
#Mann= 4 ,-1,0
       0      .1       0  166.83     .12       0   237.1    .045       0
   250.9     .12       0
Bank Sta=237.1,250.9
XS Rating Curve= 0 ,0
Exp/Cntr(USF)=0,0
Exp/Cntr=0.3,0.1

Type RM Length L Ch R = 1 ,19660   ,93,83.4,74.5
XS GIS Cut Line= 3
2243466.93832998421846.3331824092243570.47702666 421883.68333595
2243915.51760476421879.713279643
#Sta/Elev= 30
       0 2527.23    15.7 2524.52    26.8 2520.54    73.6 2496.62    82.1 2493.35
    94.9 2489.76   115.8 2487.19   183.8 2485.44   189.42484.368   195.8 2483.22
   203.8  2482.8   207.8 2482.97   210.32484.472   211.8 2485.35   215.8 2485.93
   256.6 2483.64   287.8 2487.48   299.8 2486.59   315.8 2484.19   327.8 2483.84
   343.8 2487.47   355.8 2488.55   363.8 2488.28   367.8 2487.38   375.8  2487.9
   383.8 2486.92   391.1 2486.91   411.8 2488.81   431.8 2489.79   455.1 2489.91
#Mann= 4 ,-1,0
       0      .1       0   189.4    .045       0   210.3      .1       0
  390.07     .12       0
#XS Ineff= 2 , 0
          157.87 2490.46  290.43         2489.31
Permanent Ineff=
       F       F
Bank Sta=189.4,210.3
XS Rating Curve= 0 ,0
Exp/Cntr(USF)=0,0
Exp/Cntr=0.3,0.1

Type RM Length L Ch R = 1 ,19576   ,120.3,116.9,114.1
BEGIN DESCRIPTION:
DEM issue this XS was added to avoid a gap in the floodplain
END DESCRIPTION:
XS GIS Cut Line= 6
2243454.68143955421917.0594956642243650.77614087421978.859037898
2243694.74889207421949.1477195162243711.98145673421932.509381222
 2243752.9830761421908.1461001492243902.72812074421896.261572797
#Sta/Elev= 30
       0 2524.79     5.8  2523.4    14.1 2520.23    26.7 2512.36    49.1 2500.38
    66.9 2491.92    72.9  2489.7    85.4 2488.73   102.2 2486.02     119 2485.57
   131.6 2485.96   186.1 2483.54   221.8  2484.2   227.3 2483.73   251.82483.608
   271.8 2483.26   282.9 2484.78   287.5 2484.77   306.1 2482.97   329.4 2485.59
   341.5 2483.77   357.6 2482.86   381.7 2487.46   388.1 2488.14   397.7 2488.01
   405.7 2486.85   425.8 2486.21   447.6 2488.13   465.7  2488.3   480.5 2489.39
#Mann= 3 ,-1,0
       0      .1       0   227.3    .045       0   251.8      .1       0
#XS Ineff= 2 , 0
          200.77 2487.89  328.38         2488.33
Permanent Ineff=
       F       F
Bank Sta=227.3,251.8
XS Rating Curve= 0 ,0
Exp/Cntr(USF)=0,0
Exp/Cntr=0.3,0.1

Type RM Length L Ch R = 1 ,19459   ,93.7,100.4,107.3
XS GIS Cut Line= 4
2243439.14927777421972.9537333742243739.57541437422063.081574354
2243783.33313427422019.3238544582244006.69343583421959.238627138
#Sta/Elev= 30
       0 2518.71     9.4 2515.33    20.3 2510.34    59.5  2490.6    67.9 2487.43
    72.1 2486.68   113.8 2484.35   172.3 2484.16   184.8 2483.48   201.5 2481.81
   226.6 2480.65     260 2481.15   290.1 2480.25   325.8 2481.28   335.2 2479.88
   340.9 2478.62   352.2 2477.55   359.8 2478.17   366.3 2479.77   371.1 2480.53
   388.8  2481.8   401.3 2481.48   434.4 2482.89   446.8 2482.76   459.3  2484.5
   467.5 2484.91     502 2484.43   554.5 2485.62   571.1 2486.72606.8376 2490.17
#Mann= 7 ,-1,0
       0      .1       0     310     .12       0  323.65      .1       0
  333.65     .12       0   335.2    .045       0   366.3     .12       0
  545.54      .1       0
#XS Ineff= 2 , 0
          324.17 2483.69  387.27         2483.57
Permanent Ineff=
       F       F
Bank Sta=335.2,366.3
XS Rating Curve= 0 ,0
Exp/Cntr(USF)=0,0
Exp/Cntr=0.5,0.3

Type RM Length L Ch R = 1 ,19359   ,35.3,36.4,37.9
XS GIS Cut Line= 6
2243434.57757569421999.7308455492243714.10450279422100.961391578
2243765.04632595422108.1454948442243857.78656812422099.002090687
2243919.83109633422073.531179106 2244013.8775391422006.261848519
#Sta/Elev= 30
       0 2511.21    14.5 2506.18    27.4  2499.7    51.2 2489.38      57  2487.5
    65.5 2485.86   112.3 2483.28   154.9 2483.05   163.4  2483.5   180.3 2482.94
   208.5 2480.48   235.7  2479.6   258.5 2479.37   304.2 2477.94   338.3  2477.7
   371.9  2477.7   404.1 2478.71   411.7  2477.8   415.1  2475.7   417.9 2474.79
   424.4 2474.33  430.32 2475.72   436.6 2477.38   449.2 2478.82   475.2 2479.97
   541.4 2484.38     550 2484.96   568.8 2486.56   598.8 2489.95625.0337 2491.32
#Mann= 8 ,-1,0
       0      .1       0   180.3     .05       0   235.7     .12       0
   338.3      .1       0   415.1    .045       0  430.32      .1       0
   541.4     .12       0     550      .1       0
#XS Ineff= 3 ,-1
       0     400    2485     400     406 2477.52     439     550  2479.5
Permanent Ineff=
       F       F       F
Bank Sta=415.1,430.32
XS Rating Curve= 0 ,0
Exp/Cntr(USF)=0,0
Exp/Cntr=0.5,0.3

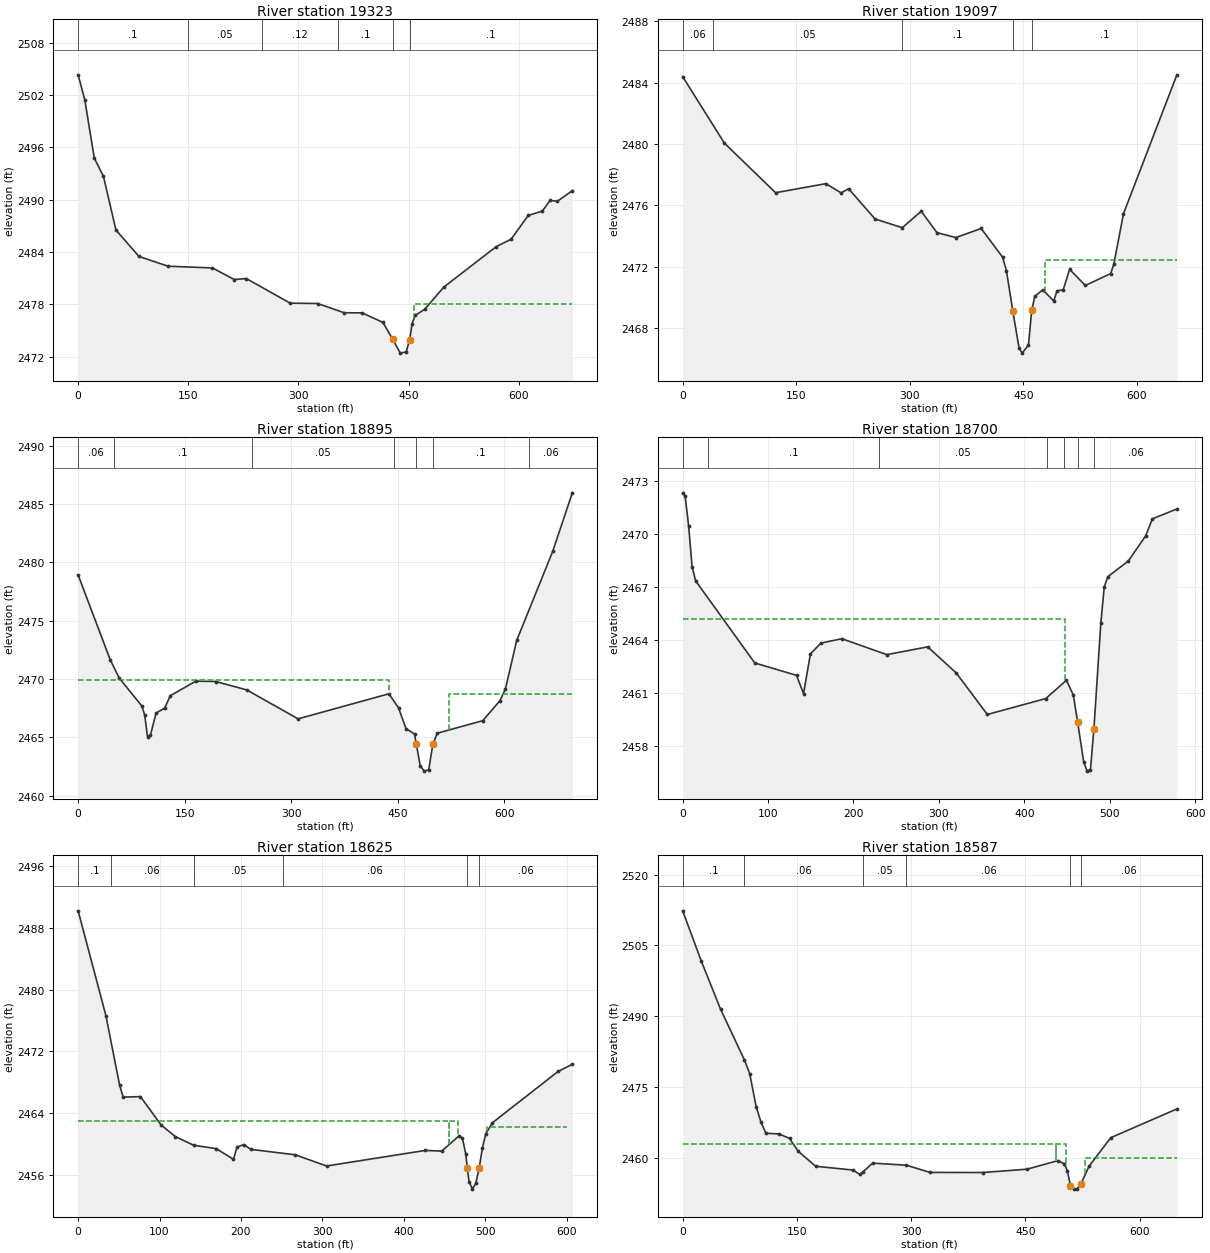
Type RM Length L Ch R = 1 ,19323   ,219,225.7,231.6
XS GIS Cut Line= 6
2243419.55626886422029.7734592092243706.26729923422130.350904941
2243808.80404585422141.4536099892243873.46097525422136.228807613
 2243927.0151996422114.0233975172244044.57325305422033.038960694
#Sta/Elev= 30
       0 2504.31     9.1 2501.43      22 2494.76    34.5 2492.66    51.5 2486.51
    82.8 2483.48   122.4 2482.36   182.9 2482.16   212.6 2480.83   229.1 2480.94
   288.7 2478.12     326 2478.08   362.4 2477.02   386.5 2477.01   414.9 2475.92
     428 2474.02   438.6 2472.39   446.6 2472.53   451.4 2473.93   454.6 2475.74
   458.7 2476.71     472 2477.43   497.8 2479.96   568.8 2484.58   589.5 2485.46
   612.8 2488.18     632 2488.69   642.6  2489.9   652.5 2489.81672.8364 2491.02
#Mann= 6 ,-1,0
       0      .1       0     150     .05       0     250     .12       0
  353.84      .1       0     428    .045       0   451.4      .1       0
#XS Ineff= 2 , 0
             419  2474.9     457            2478
Permanent Ineff=
       F       F
Bank Sta=428,451.4
XS Rating Curve= 0 ,0
Exp/Cntr(USF)=0,0
Exp/Cntr=0.5,0.3

Type RM Length L Ch R = 1 ,19097   ,206.4,201.5,196.6
XS GIS Cut Line= 3
 2243424.5293275422139.7693458492243661.04301529422316.258726508
2244004.16703962422417.493751962
#Sta/Elev= 30
       0 2484.39    55.1 2480.06   122.7 2476.83   189.2 2477.42   209.2 2476.82
   219.2 2477.09   254.1 2475.12     290 2474.55   315.1 2475.62   335.9 2474.23
   360.9 2473.91   394.3  2474.5   422.6 2472.63   427.7 2471.74     436 2469.15
   444.3 2466.72   448.5 2466.38   456.8 2466.91     461 2469.16   465.2 2470.08
   475.5  2470.5   490.2 2469.78   494.4 2470.43   502.7 2470.51   511.1 2471.84
   531.9 2470.79   565.3 2471.56   569.5 2472.17   582.3 2475.47652.8521 2484.51
#Mann= 5 ,-1,0
       0     .06       0      40     .05       0     290      .1       0
     436    .045       0     461      .1       0
#XS Ineff= 2 , 0
                          477.97         2472.44
Permanent Ineff=
       F       F
Bank Sta=436,461
XS Rating Curve= 0 ,0
Exp/Cntr(USF)=0,0
Exp/Cntr=0.3,0.1

Type RM Length L Ch R = 1 ,18895   ,193.1,195,196.5
XS GIS Cut Line= 3
2243314.33545024422558.1477253812243508.74253452  422557.2518402
2244010.43823589422559.939495743
#Sta/Elev= 30
       0 2478.91    45.1 2471.66    57.8 2470.08    89.8 2467.68    93.8  2466.9
    97.8 2465.03   101.8 2465.17   109.8 2467.08   121.8 2467.49   129.8 2468.56
   165.8 2469.81   193.8 2469.78   237.5 2469.06   309.8 2466.58   437.8 2468.73
   451.3 2467.52   461.8 2465.75   473.8 2465.28   476.3 2464.45   481.8 2462.56
   487.5  2462.1   493.8 2462.21   499.6 2464.39   505.8 2465.35   569.8 2466.42
   593.8 2468.11   601.8 2469.12   617.8 2473.31   668.5 2480.94696.1121 2485.95
#Mann= 7 ,-1,0
       0     .06       0      50      .1       0  244.41     .05       0
  444.41      .1       0   476.3    .045       0   499.6      .1       0
  634.41     .06       0
#XS Ineff= 2 , 0
          437.35 2469.95  521.75         2468.67
Permanent Ineff=
       F       F
Bank Sta=476.3,499.6
XS Rating Curve= 0 ,0
Exp/Cntr(USF)=0,0
Exp/Cntr=0.3,0.1

Type RM Length L Ch R = 1 ,18700   ,79.3,75.5,71.1
XS GIS Cut Line= 3
2243329.33590313422786.8529325042243610.88744114422731.600647381
2243900.66804291422765.692482882
#Sta/Elev= 30
       0 2472.31     2.9 2472.12       7 2470.42      11 2468.14    15.1 2467.34
    84.4  2462.7   133.3    2462   141.5 2460.97   149.6 2463.22   161.9 2463.82
   186.3 2464.07     239 2463.17   286.9 2463.61   320.4 2462.13   356.7 2459.79
   425.2 2460.69   449.3 2461.72   457.4 2460.89   462.5 2459.35   469.5 2457.13
   473.5 2456.59   477.5 2456.68   481.5 2458.97   489.6 2464.94   493.6 2466.99
   497.7 2467.57   521.8 2468.46     542 2469.87     550 2470.84578.7009  2471.4
#Mann= 7 ,-1,0
       0     .08       0      30      .1       0     230     .05       0
  426.92      .1       0  446.92     .06       0   462.5    .045       0
   481.5     .06       0
#XS Ineff= 2 , 0
          447.55  2465.2
Permanent Ineff=
       F       F
Bank Sta=462.5,481.5
XS Rating Curve= 0 ,0
Exp/Cntr(USF)=0,0
Exp/Cntr=0.5,0.3

Type RM Length L Ch R = 1 ,18625   ,38.5,38.4,38.7
XS GIS Cut Line= 6
2243320.02432114422977.1675587032243453.90988202422930.144337322
2243660.28957585422858.9564049532243766.06131046422830.609287817
2243808.57765269422820.8214503112243901.47354156422809.697257074
#Sta/Elev= 30
       0 2490.24    34.1 2476.65      51 2467.62    55.3 2466.08    76.5 2466.15
   101.9 2462.47   119.3 2460.97   141.9 2459.84   169.6  2459.4   190.8 2458.02
   195.1  2459.6   203.5 2459.93     212 2459.31   266.7  2458.6   305.1 2457.15
   426.4 2459.17   446.5 2459.08   467.8 2461.06   471.9 2460.75     476 2458.73
  477.86 2456.95   480.1 2455.13   484.2 2454.15   488.3 2454.89   492.4 2456.83
   496.5  2459.5   500.6 2461.33   508.8 2462.76   589.5 2469.42606.9081 2470.33
#Mann= 6 ,-1,0
       0      .1       0      40     .06       0   141.9     .05       0
   251.9     .06       0  477.86    .045       0   492.4     .06       0
#XS Ineff= 3 ,-1
       0     455    2463     455     467    2463     502     600 2462.26
Permanent Ineff=
       F       F       F
Bank Sta=477.86,492.4
XS Rating Curve= 0 ,0
Exp/Cntr(USF)=0,0
Exp/Cntr=0.5,0.3

Type RM Length L Ch R = 1 ,18587   ,172.1,172.3,169.8
XS GIS Cut Line= 6
 2243285.4100054423026.1500809742243628.76003447422902.412912955
2243699.28530067 422879.260365072243801.65870046422859.517984942
2243818.86718618422856.8714101122243905.29723317422839.203392665
#Sta/Elev= 30
       0 2512.32    24.2 2501.77    49.7 2491.49      81 2480.75      88 2477.82
    96.5 2470.83   102.9 2467.51   109.3 2465.19   126.3 2465.05   140.3  2464.1
   151.8 2461.36   174.7 2458.19     224 2457.39   232.5 2456.46   236.7 2456.97
   249.4 2458.86   293.7 2458.42   324.9 2456.89     394 2456.87   452.1 2457.57
   492.9 2459.39   501.1  2458.7   505.2 2457.24   509.3 2454.03   513.3 2453.35
   517.8 2453.44     523 2454.45   533.8 2458.22   562.2 2464.25   649.1 2470.34
#Mann= 6 ,-1,0
       0      .1       0      81     .06       0   236.7     .05       0
   293.7     .06       0   509.3    .045       0     523     .06       0
#XS Ineff= 3 ,-1
       0     490    2463     490     503    2463     529 649.095    2460
Permanent Ineff=
       F       F       F
Bank Sta=509.3,523
XS Rating Curve= 0 ,0
Exp/Cntr(USF)=0,0
Exp/Cntr=0.5,0.3

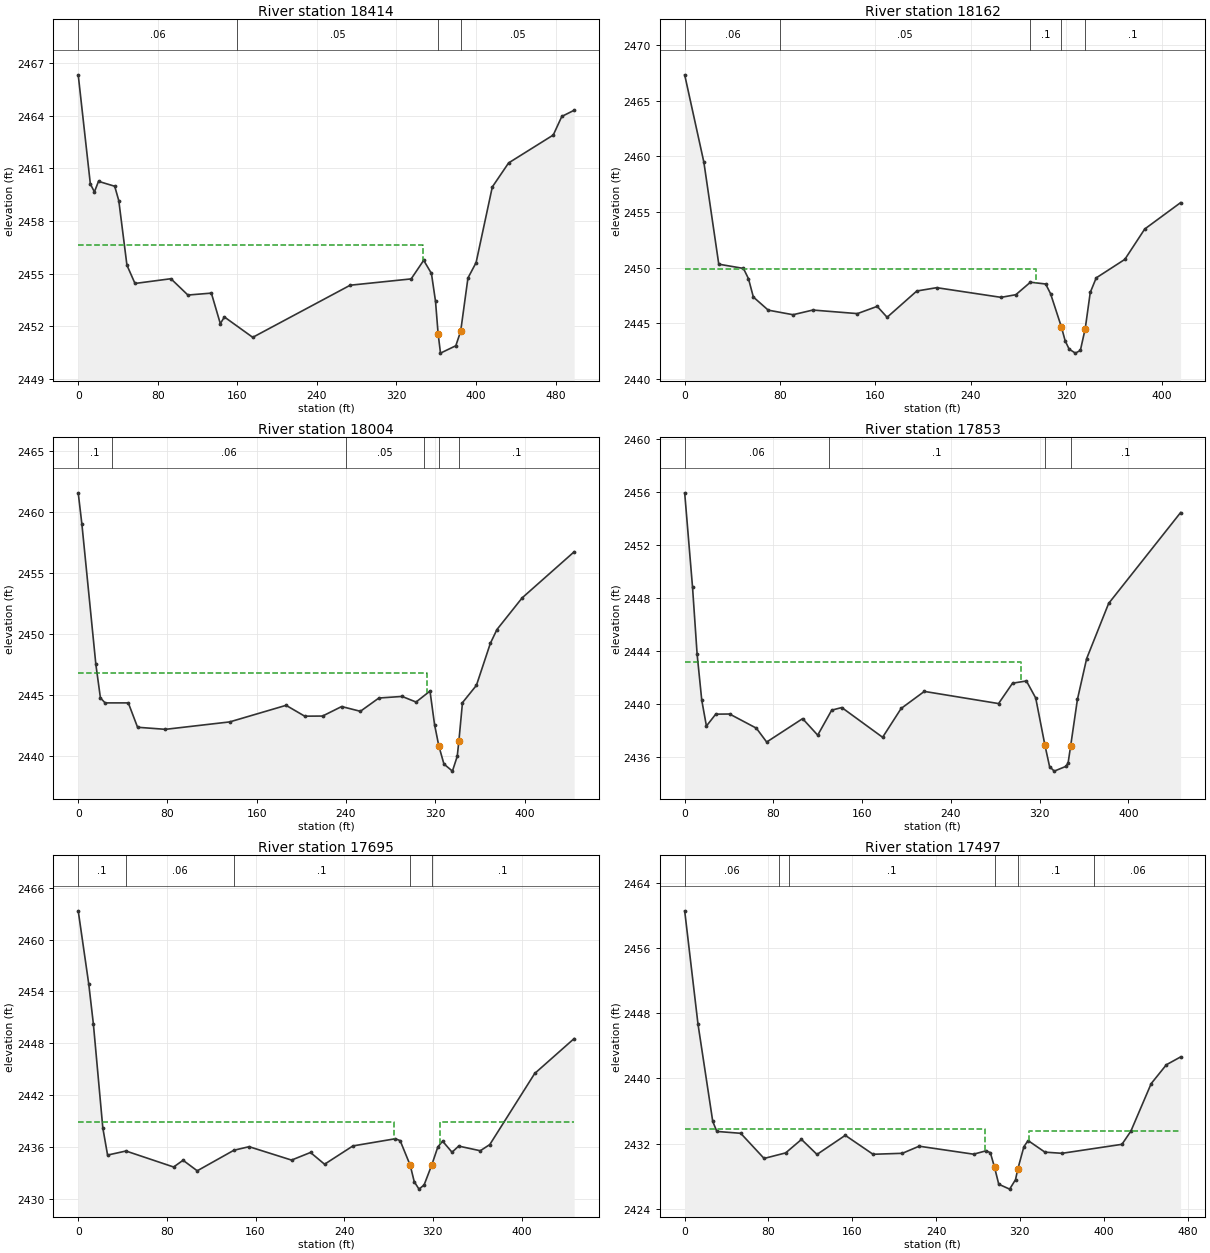
Type RM Length L Ch R = 1 ,18414   ,253.9,252,251.9
XS GIS Cut Line= 2
2243404.20395307423107.1985309332243892.72099468423007.145507091
#Sta/Elev= 30
       0 2466.33    12.2 2460.11    16.3 2459.66    20.4 2460.26    36.7 2459.98
    40.8 2459.16      49 2455.48    57.1 2454.44    93.2 2454.71   110.3 2453.78
   133.9 2453.89   142.9 2452.15     147 2452.53   175.5 2451.37   273.5 2454.34
   334.8  2454.7   347.4 2455.76   355.2 2455.01   359.3 2453.42   361.9 2451.58
   364.3 2450.47   379.7 2450.89   384.6 2451.72   391.9 2454.75   400.1 2455.63
   416.4 2459.94   432.8 2461.31   477.7  2462.9   486.3 2463.96   498.7 2464.31
#Mann= 4 ,-1,0
       0     .06       0     160     .05       0   361.9    .045       0
   384.6     .05       0
#XS Ineff= 2 , 0
          347.04 2456.65
Permanent Ineff=
       F       F
Bank Sta=361.9,384.6
XS Rating Curve= 0 ,0
Exp/Cntr(USF)=0,0
Exp/Cntr=0.3,0.1

Type RM Length L Ch R = 1 ,18162   ,158.4,158.5,158
XS GIS Cut Line= 2
2243476.68648403423371.3519972162243877.15643222423258.848517048
#Sta/Elev= 30
       0 2467.31    16.1 2459.46    28.6  2450.3    49.3 2449.92    53.5    2449
    57.6 2447.35    70.1 2446.17    90.9 2445.76   107.5 2446.18   144.9 2445.86
   161.5 2446.51   169.8 2445.53   194.7 2447.89   211.4 2448.19   265.4 2447.32
   277.8 2447.56     290 2448.68   302.8 2448.52   306.9 2447.65     316 2444.66
   319.2  2443.4   322.5 2442.67   327.7 2442.31   331.9 2442.55     336 2444.52
   340.2 2447.76   345.2 2449.07   369.2 2450.73   385.9 2453.46     416 2455.83
#Mann= 5 ,-1,0
       0     .06       0      80     .05       0     290      .1       0
     316    .045       0     336      .1       0
#XS Ineff= 2 , 0
          294.65 2449.84
Permanent Ineff=
       F       F
Bank Sta=316,336
XS Rating Curve= 0 ,0
Exp/Cntr(USF)=0,0
Exp/Cntr=0.3,0.1

Type RM Length L Ch R = 1 ,18004   ,150.8,150.7,150.7
XS GIS Cut Line= 2
2243524.99341092423521.8517199042243952.39358641423399.918181191
#Sta/Elev= 30
       0 2461.58     3.3 2459.01    15.8 2447.51    19.9 2444.75    24.1 2444.34
    44.9 2444.34    53.2 2442.34    78.2 2442.17   135.8 2442.78   186.3 2444.14
     203 2443.25     219 2443.26   236.1 2444.04   252.9 2443.65   269.5 2444.74
   290.3 2444.87   302.8 2444.41   315.3 2445.31   319.4 2442.55   323.2 2440.81
   327.8 2439.32   335.4 2438.74   339.7 2439.95   341.2 2441.22   344.4 2444.36
   356.9 2445.78   369.4 2449.23   375.3 2450.36   397.9 2452.96   444.5 2456.74
#Mann= 6 ,-1,0
       0      .1       0      30     .06       0     240     .05       0
     310      .1       0   323.2    .045       0   341.2      .1       0
#XS Ineff= 2 , 0
          312.96 2446.76
Permanent Ineff=
       F       F
Bank Sta=323.2,341.2
XS Rating Curve= 0 ,0
Exp/Cntr(USF)=0,0
Exp/Cntr=0.3,0.1

Type RM Length L Ch R = 1 ,17853   ,157.6,158,156.9
XS GIS Cut Line= 2
2243569.41725894423670.9860782482243997.23436606 423541.29921228
#Sta/Elev= 30
       0 2455.96     7.1  2448.8    11.2 2443.76    15.4 2440.27    19.6 2438.32
      28 2439.22    40.5 2439.23    64.6 2438.16    73.9 2437.11   106.3 2438.88
   119.9 2437.63   132.5 2439.52   141.6 2439.72   178.4 2437.47   195.1 2439.65
     216 2440.94   282.9 2440.02   295.5 2441.56     308 2441.73   316.4 2440.44
   324.7 2436.87   328.9 2435.25   333.1 2434.91   343.6 2435.27   345.6 2435.53
  347.89 2436.82     354 2440.34   362.3 2443.42   382.1 2447.59     447 2454.47
#Mann= 4 ,-1,0
       0     .06       0     130      .1       0   324.7    .045       0
  347.89      .1       0
#XS Ineff= 2 , 0
          302.82 2443.15
Permanent Ineff=
       F       F
Bank Sta=324.7,347.89
XS Rating Curve= 0 ,0
Exp/Cntr(USF)=0,0
Exp/Cntr=0.3,0.1

Type RM Length L Ch R = 1 ,17695   ,192.1,198.5,204.2
XS GIS Cut Line= 2
2243619.28195418423832.3598244892244039.67383885423679.118650659
#Sta/Elev= 30
       0 2463.32     9.5 2454.86    13.7 2450.21    22.2  2438.2    26.5 2435.06
    43.1 2435.53    86.1 2433.68    94.6 2434.46   107.4 2433.24   140.5 2435.62
   154.2 2436.03   192.5 2434.48   209.6 2435.36   222.3    2434   247.9 2436.12
   286.2 2436.95   290.5 2436.73   299.6 2433.87   303.2 2431.98   307.5 2431.12
   312.1  2431.6   319.12433.946   324.5    2436   328.8 2436.67   337.3 2435.39
   343.3  2436.1   362.8 2435.56   371.4 2436.28   411.9  2444.5   447.5 2448.54
#Mann= 5 ,-1,0
       0      .1       0    43.1     .06       0   140.5      .1       0
   299.6    .045       0   319.1      .1       0
#XS Ineff= 2 , 0
          285.35 2438.84  326.76         2438.93
Permanent Ineff=
       F       F
Bank Sta=299.6,319.1
XS Rating Curve= 0 ,0
Exp/Cntr(USF)=0,0
Exp/Cntr=0.3,0.1

Type RM Length L Ch R = 1 ,17497   ,171.3,164.8,158.7
XS GIS Cut Line= 5
2243676.13216081423974.1892723732243813.67508335423906.593391637
2243991.18774406423911.2957137762244079.35628415423897.188747361
 2244123.4405542423867.211443731
#Sta/Elev= 30
       0 2460.54    12.7 2446.67    26.8 2434.73    30.7 2433.51    53.5 2433.28
    75.8  2430.2    96.4 2430.88   111.5 2432.53   126.3 2430.69   153.3 2433.03
   179.8 2430.71   207.8 2430.83   223.8  2431.7   275.8 2430.72   287.8 2431.14
   291.8  2430.9   295.8  2429.1   299.8 2427.04   310.2 2426.44   315.8  2427.6
     318 2428.91   323.8 2431.64   327.8 2432.39   343.9 2430.97   360.2 2430.83
   417.4 2431.93   425.9 2433.54   445.3 2439.37   459.8 2441.68   473.4 2442.64
#Mann= 6 ,-1,0
       0     .06       0      90     .05       0     100      .1       0
   295.8    .045       0     318      .1       0  390.83     .06       0
#XS Ineff= 2 ,-1
       0 286.741 2433.79 328.708 473.369 2433.59
Permanent Ineff=
       F       F
Bank Sta=295.8,318
XS Rating Curve= 0 ,0
Exp/Cntr(USF)=0,0
Exp/Cntr=0.3,0.1