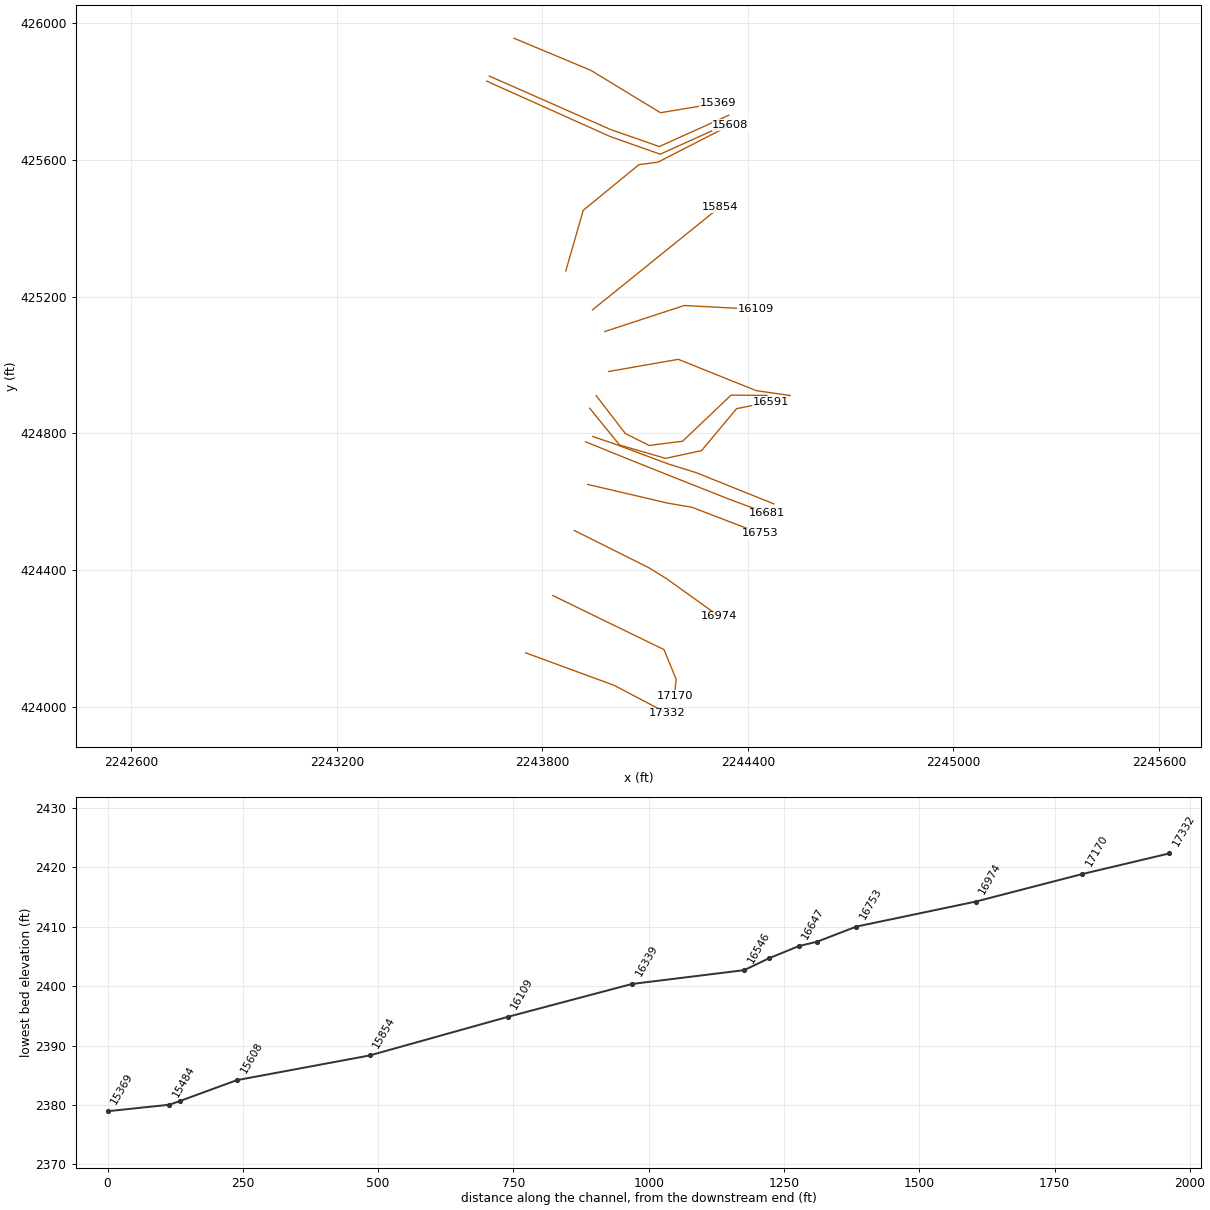
HEC-RAS study CMMNGSCK.prj: CMMNGSCK

--- CMMNGSCK.g01 (geometry) --- (continued)

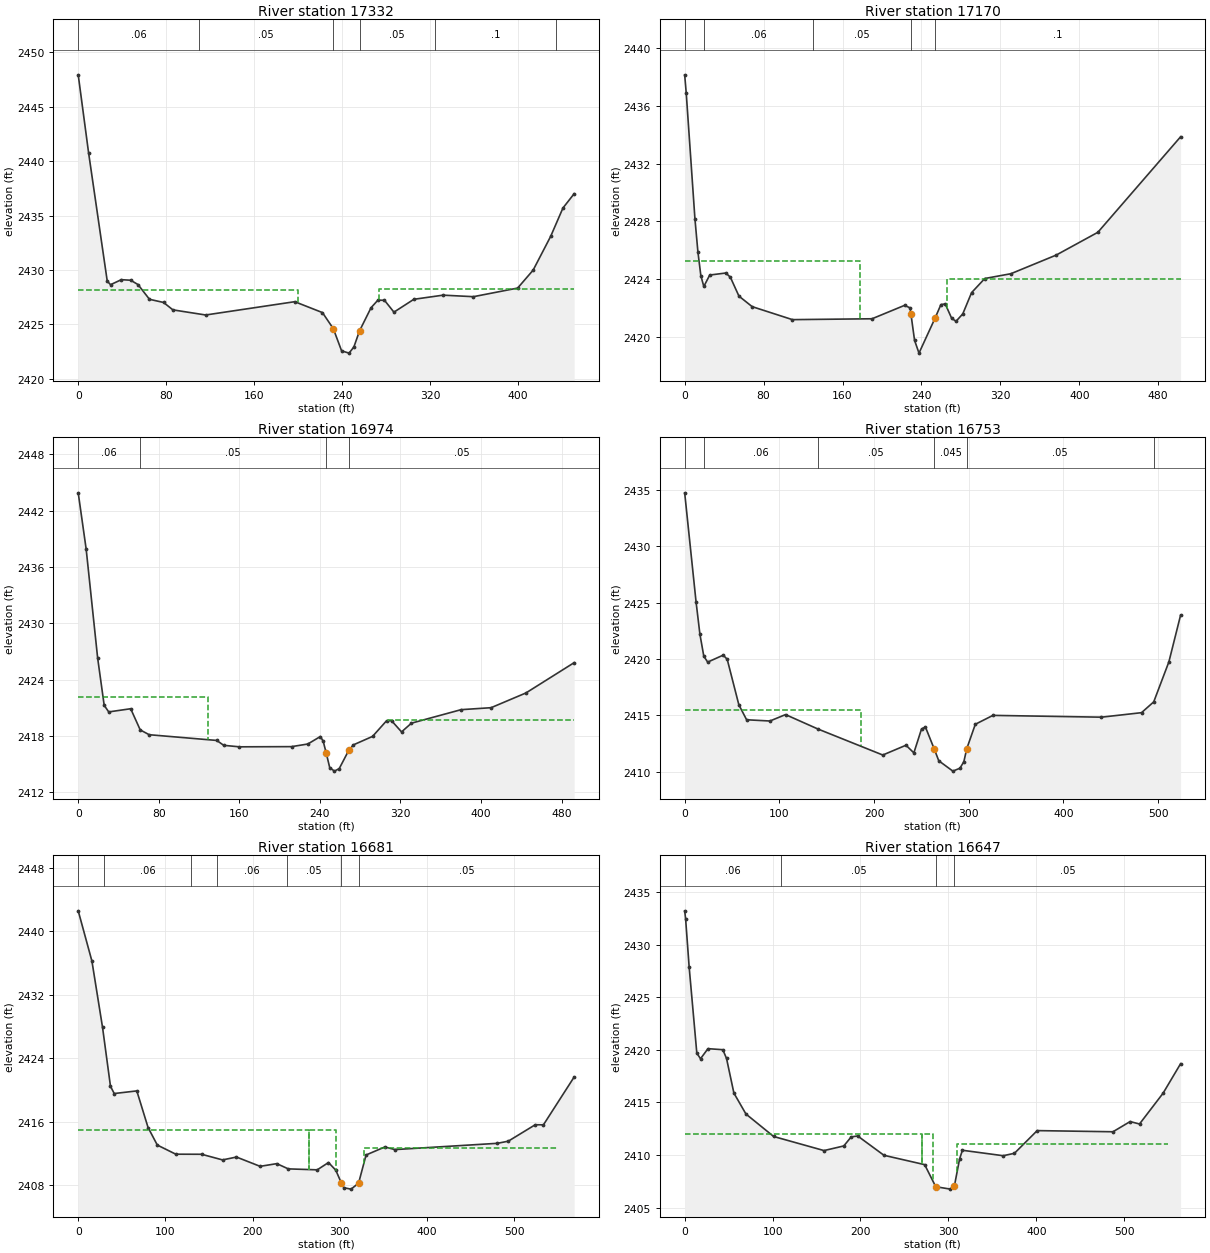
Type RM Length L Ch R = 1 ,17332   ,163.2,161.6,159.7
XS GIS Cut Line= 3
2243751.36931502424158.1676260262244008.82145208424063.533392996
2244165.17366317 423981.24275558
#Sta/Elev= 30
       0 2447.91     9.4 2440.78    26.4 2428.98    29.4 2428.65    39.2 2429.11
    47.7 2429.06    54.4 2428.66    64.8 2427.31    77.6 2427.02    86.1 2426.34
   115.9 2425.87   196.9 2427.09   222.1 2426.09     232 2424.61   239.5 2422.58
   246.3 2422.37   250.7 2422.94   255.8 2424.41   266.3 2426.54   272.5 2427.23
   278.5 2427.22   287.1 2426.13   305.2 2427.31   331.8 2427.69   359.4 2427.55
   399.6 2428.34   413.7 2429.99   429.6 2433.08   440.8 2435.69450.9796    2437
#Mann= 6 ,-1,0
       0     .06       0     110     .05       0     232    .045       0
   255.8     .05       0  324.29      .1       0  434.29     .05       0
#XS Ineff= 2 , 0
          199.72 2428.14  273.52         2428.29
Permanent Ineff=
       F       F
Bank Sta=232,255.8
XS Rating Curve= 0 ,0
Exp/Cntr(USF)=0,0
Exp/Cntr=0.3,0.1

Type RM Length L Ch R = 1 ,17170   ,197.7,196.6,194.6
XS GIS Cut Line= 4
 2243830.7210011424325.6878521952244155.18122863424167.572270302
2244190.44864466424081.1671010142244185.74632253424032.968299099
#Sta/Elev= 30
       0 2438.16     1.6 2436.87    10.4 2428.18    13.4  2425.9    16.4 2424.24
    19.4  2423.5    25.4 2424.29    41.7 2424.43    46.3 2424.14      55 2422.83
    68.4  2422.1   109.2  2421.2   189.9 2421.26   222.9 2422.19   228.6 2422.01
   229.4 2421.56     233 2419.77   237.5 2418.88   253.7 2421.29   259.7 2422.24
   264.1 2422.29   270.7 2421.28   275.1 2421.09   281.9  2421.6   290.8 2423.07
   304.2 2424.05   330.6 2424.38   376.5 2425.67   418.8 2427.25502.6894 2433.87
#Mann= 5 ,-1,0
       0      .1       0      20     .06       0     130     .05       0
   229.4    .045       0   253.7      .1       0
#XS Ineff= 2 , 0
          177.41 2425.24  266.37            2424
Permanent Ineff=
       F       F
Bank Sta=229.4,253.7
XS Rating Curve= 0 ,0
Exp/Cntr(USF)=0,0
Exp/Cntr=0.3,0.1

Type RM Length L Ch R = 1 ,16974   ,214.8,220.4,226.9
XS GIS Cut Line= 4
2243893.09712884424516.0185572382244110.64188759424407.159288552
2244163.41029237424374.4744443782244315.37424539424265.201491426
#Sta/Elev= 30
       0 2443.91     7.9 2437.91    19.3  2426.3    25.8 2421.26    30.3 2420.56
    52.1  2420.9    61.6 2418.64    70.5 2418.13   137.6 2417.52   144.5    2417
     160 2416.84   211.9 2416.86     228 2417.14   240.5 2417.94   243.3 2417.43
246.22792416.202   249.8 2414.61   254.5 2414.25   259.2 2414.52   268.6 2416.45
   273.3 2417.05   292.3 2417.95   306.3 2419.63   311.2 2419.62   321.1 2418.43
   330.9 2419.36   380.2  2420.8     410 2421.01   444.6 2422.58   492.5 2425.81
#Mann= 4 ,-1,0
       0     .06       0    61.6     .05       0246.2279    .045       0
   268.6     .05       0
#XS Ineff= 2 , 0
          128.74 2422.12     308         2419.67
Permanent Ineff=
       F       F
Bank Sta=246.2279,268.6
XS Rating Curve= 0 ,0
Exp/Cntr=0.3,0.1

Type RM Length L Ch R = 1 ,16753   ,74,71.7,68.9
XS GIS Cut Line= 4
2243932.50761387424650.6035294392244164.73838215424596.174443122
2244236.58477609424583.8371835572244434.70665029424507.636462713
#Sta/Elev= 30
       0 2434.75      12 2425.08    16.1 2422.19    20.2 2420.24    24.3 2419.72
    40.7 2420.34    44.9 2419.97    57.2 2415.93    65.4  2414.6      90 2414.49
   106.5 2415.06   140.7 2413.78   209.2 2411.47   233.7 2412.34     242 2411.66
   250.1 2413.78   254.2 2413.96   263.6 2411.99   268.3 2410.96   283.2 2410.04
   290.7  2410.3   294.8 2410.88   297.9 2412.04   306.9  2414.2   325.5 2414.99
   440.1 2414.83   482.4 2415.23   495.3 2416.19   511.3 2419.74523.6925  2423.9
#Mann= 6 ,-1,0
       0      .1       0    20.2     .06       0   140.7     .05       0
   263.6    .045       0   297.9     .05       0   495.3      .1       0
#XS Ineff= 2 , 0
          186.38 2415.43
Permanent Ineff=
       F       F
Bank Sta=263.6,297.9
XS Rating Curve= 0 ,0
Exp/Cntr(USF)=0,0
Exp/Cntr=0.5,0.3

Type RM Length L Ch R = 1 ,16681   ,33.8,34.8,36
XS GIS Cut Line= 5
 2243925.9430244 424775.347406652244045.85223892424726.560814468
 2244189.8608544424668.957368276 2244353.2665487424604.300438877
2244454.95426493424566.681861773
#Sta/Elev= 30
       0 2442.57    15.7 2436.25    27.9 2427.89      37 2420.47    41.3 2419.56
    67.2 2419.89    80.1 2415.28    90.7 2413.07   111.9 2411.92   141.5 2411.91
   165.5  2411.2   181.5 2411.56   208.6 2410.39   227.7 2410.73   240.9 2410.07
   274.1 2409.95     287 2410.87   295.4  2409.9   301.6 2408.33   304.7 2407.69
   312.9 2407.52   321.5 2408.27   330.1 2411.82   351.6 2412.83   363.2  2412.5
   480.8 2413.29   493.2 2413.56   524.1 2415.63   533.5 2415.62568.7117 2421.64
#Mann= 7 ,-1,0
       0      .1       0      30     .06       0  129.45     .05       0
  159.45     .06       0  239.45     .05       0   301.6    .045       0
   321.5     .05       0
#XS Ineff= 3 ,-1
       0     265    2415     265   295.6    2415   327.5     550 2412.67
Permanent Ineff=
       F       F       F
Bank Sta=301.6,321.5
XS Rating Curve= 0 ,0
Exp/Cntr(USF)=0,0
Exp/Cntr=0.5,0.3

Type RM Length L Ch R = 1 ,16647   ,50.2,55.2,60.7
XS GIS Cut Line= 5
2243947.10347402424790.6299535992244012.93598395424768.293923443
2244165.17366317424711.2782675192244250.99104219424684.239915225
2244475.52692429424593.720214067
#Sta/Elev= 30
       0 2433.24     1.1 2432.44     5.1 2427.88    13.8  2419.7      18 2419.16
    26.5 2420.12    43.4 2420.02    47.6 2419.19      56 2415.89    69.7  2413.9
   101.2 2411.76   158.5 2410.42     181 2410.86   189.4 2411.72   196.8 2411.81
   226.7 2409.97     273 2409.08   285.6 2406.98   302.3 2406.75   306.9 2407.09
   312.7 2409.61   315.9 2410.45   362.3 2409.93   375.1 2410.16     401 2412.32
   487.2 2412.21   506.7 2413.18   517.4 2412.95   544.2 2415.88564.1541 2418.69
#Mann= 4 ,-1,0
       0     .06       0  109.52     .05       0   285.6    .045       0
   306.9     .05       0
#XS Ineff= 3 ,-1
       0     270    2412     270   282.6    2412   309.9     550    2411
Permanent Ineff=
       F       F       F
Bank Sta=285.6,306.9
XS Rating Curve= 0 ,0
Exp/Cntr(USF)=0,0
Exp/Cntr=0.5,0.3

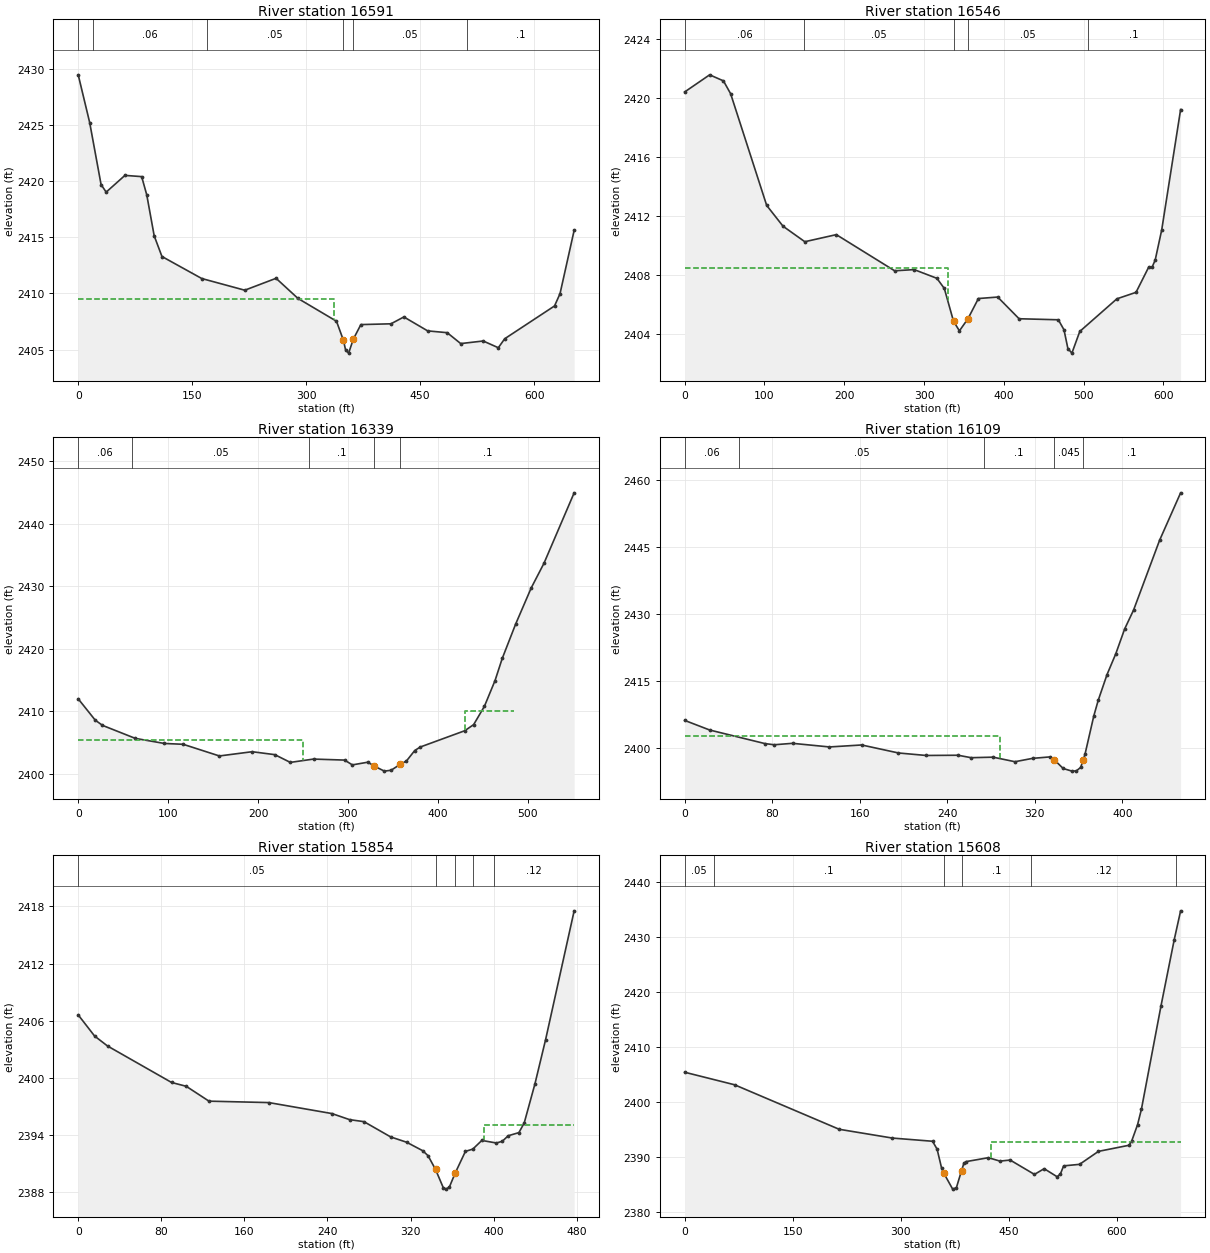
Type RM Length L Ch R = 1 ,16591   ,38.4,45.4,53.3
XS GIS Cut Line= 6
2243938.15271898424873.2860641332244025.30558041424765.891247789
2244159.40853171424726.8130292762244264.55424195 424749.30409029
2244367.01424359424872.163829739 2244465.9241908424891.702841198
#Sta/Elev= 30
       0 2429.46    15.1 2425.21    30.1 2419.69    36.8 2419.02    61.5 2420.51
    83.5  2420.4    90.2 2418.78     100 2415.13   110.2 2413.29   162.6 2411.33
   219.2 2410.29   260.4 2411.35   289.2 2409.56   339.9 2407.53   349.1 2405.82
   351.9 2404.97   355.9 2404.69   362.1 2405.94     372 2407.23   411.6  2407.3
   428.6 2407.91   459.9 2406.67   485.6 2406.51   503.4 2405.54     533 2405.77
   552.9 2405.17   561.3 2405.97   626.9 2408.89   634.1 2409.98   652.7 2415.62
#Mann= 6 ,-1,0
       0      .1       0      20     .06       0  169.13     .05       0
   349.1    .045       0   362.1     .05       0  511.24      .1       0
#XS Ineff= 3 ,-1
       0 336.975 2409.51 383.971  399.97 2406.36  399.97   652.7 2406.36
Permanent Ineff=
       F       F       F
Bank Sta=349.1,362.1
XS Rating Curve= 0 ,0
Exp/Cntr(USF)=0,0
Exp/Cntr=0.5,0.3

Type RM Length L Ch R = 1 ,16546   ,218.7,207.5,194.1
XS GIS Cut Line= 6
 2243957.0834333424910.2526390572244042.30714415424799.318981917
2244111.81922116424764.5629434142244209.42179504424776.941806442
2244350.82649963424911.6809694072244455.61495212424910.848359169
#Sta/Elev= 30
       0 2420.41    31.3 2421.57    48.6 2421.16    57.6 2420.29   102.8 2412.72
   123.3 2411.31   150.6 2410.26   190.1 2410.74   263.2 2408.29   287.7 2408.37
   316.2 2407.78   325.5 2407.09     337 2404.87   344.4 2404.22   355.1 2405.04
   368.2 2406.41   392.4 2406.51   419.2 2405.04   468.4 2404.97   475.5 2404.29
   480.4 2403.02   485.4 2402.71   495.3 2404.18   541.8 2406.39   565.8 2406.83
   581.8 2408.55   585.8 2408.52   589.8 2409.01     598 2411.06   621.7 2419.22
#Mann= 5 ,-1,0
       0     .06       0  149.89     .05       0     337    .045       0
   355.1     .05       0  505.29      .1       0
#XS Ineff= 3 ,-1
       0 329.987  2408.5 361.986 384.985  2405.5 384.985   621.7  2405.5
Permanent Ineff=
       F       F       F
Bank Sta=337,355.1
XS Rating Curve= 0 ,0
Exp/Cntr(USF)=0,0
Exp/Cntr=0.3,0.1

Type RM Length L Ch R = 1 ,16339   ,220.1,229.4,233.9
XS GIS Cut Line= 5
2243993.52937554424980.7870903772244196.74569881425016.314313115
2244363.93937483424949.0449825292244424.02460215424924.880271541
2244523.29584728424910.512065008
#Sta/Elev= 30
       0 2411.96    18.9 2408.55      27 2407.71    63.6 2405.62    95.9 2404.81
   116.7 2404.68     157 2402.81   193.5 2403.49   218.6 2403.02   235.9 2401.78
   261.7 2402.31   296.2 2402.15   304.9 2401.38   322.1 2401.81   329.5 2401.17
   340.5 2400.38     348 2400.52   358.3 2401.48   365.1 2402.01   374.3 2403.68
   380.4 2404.24   429.9 2406.85   439.8 2407.83   451.8 2410.77   463.6 2414.89
   471.6 2418.43   486.5 2423.93   503.8 2429.72     518 2433.67551.5855 2444.96
#Mann= 5 ,-1,0
       0     .06       0      60     .05       0   256.3      .1       0
   329.5    .045       0   358.3      .1       0
#XS Ineff= 2 ,-1
       0     250 2405.34 430.513 484.763    2410
Permanent Ineff=
       F       F
Bank Sta=329.5,358.3
XS Rating Curve= 0 ,0
Exp/Cntr(USF)=0,0
Exp/Cntr=0.3,0.1

Type RM Length L Ch R = 1 ,16109   ,240.6,255.3,266
XS GIS Cut Line= 3
2243982.45802647425097.6920435332244214.37940682425173.711484682
2244423.37150185425162.608779634
#Sta/Elev= 30
       0 2406.21    22.9 2404.05    73.4 2401.01    81.8 2400.75    98.6 2401.07
   132.3 2400.26   161.8  2400.7   195.4 2398.91   220.7 2398.35   249.9  2398.4
   261.9 2397.85   281.9 2397.97   301.9 2396.95     318  2397.7     334 2398.03
   337.6 2397.44     346 2395.43     354 2394.84     358 2394.89     362 2395.68
   364.2 2397.27     366 2398.68     374 2407.22     378 2410.69   386.1 2416.49
   394.1 2421.15   402.2 2426.71   410.4 2430.97   434.1 2446.56453.3492 2457.21
#Mann= 5 ,-1,0
       0     .06       0      50     .05       0  274.06      .1       0
   337.6    .045       0   364.2      .1       0
#XS Ineff= 2 , 0
          288.45 2402.75
Permanent Ineff=
       F       F
Bank Sta=337.6,364.2
XS Rating Curve= 0 ,0
Exp/Cntr(USF)=0,0
Exp/Cntr=0.3,0.1

Type RM Length L Ch R = 1 ,15854   ,245.2,245.3,245.3
XS GIS Cut Line= 2
  2243946.270581425160.8612284852244317.56925374425461.075615344
#Sta/Elev= 30
       0 2406.62    15.8  2404.4    28.2 2403.36    89.9 2399.53     104 2399.13
   125.9 2397.57   183.6 2397.42   244.2 2396.27   261.3 2395.63   275.1 2395.42
   300.8 2393.82   316.2 2393.26   331.7 2392.37   336.8 2391.85     344 2390.41
   351.4 2388.51   354.3 2388.34   357.4 2388.57   362.8 2389.99   372.8  2392.3
   379.9 2392.54   388.6 2393.45   402.6 2393.18   408.3 2393.36     414 2393.94
   424.3 2394.27   429.4 2395.28   439.7 2399.37     450 2404.03477.4844 2417.54
#Mann= 5 ,-1,0
       0     .05       0     344    .045       0   362.8     .05       0
     380      .1       0     400     .12       0
#XS Ineff= 2 , 0
                           390.7         2395.11
Permanent Ineff=
       F       F
Bank Sta=344,362.8
XS Rating Curve= 0 ,0
Exp/Cntr(USF)=0,0
Exp/Cntr=0.3,0.1

Type RM Length L Ch R = 1 ,15608   ,121.6,104.6,83.5
XS GIS Cut Line= 5
2243868.32857025425274.6386464732243919.39402557425452.023912314
2244082.04914726425585.5520150032244137.71855652 425592.96098545
2244348.58125981425701.264544982
#Sta/Elev= 30
       0 2405.45    69.2 2403.17   214.4 2395.07   288.3 2393.47     344 2392.89
   350.3 2391.45   356.6 2387.97   359.3 2387.15   371.9 2384.18   377.1 2384.45
   384.2 2387.54   387.4 2388.85   390.6 2389.19   421.5  2389.9   437.5 2389.28
   451.7 2389.47   485.4 2386.86   498.9  2387.9   516.9 2386.43   521.4 2386.94
   525.9 2388.41     548 2388.69   574.2 2391.05   616.6 2392.16   620.3 2392.92
   628.5 2395.91   633.8 2398.69   661.1 2417.58   679.3 2429.52688.2431 2434.82
#Mann= 6 ,-1,0
       0     .05       0      40      .1       0   359.3    .045       0
   384.2      .1       0  481.19     .12       0  681.19      .1       0
#XS Ineff= 2 , 0
                          424.73         2392.74
Permanent Ineff=
       F       F
Bank Sta=359.3,384.2
XS Rating Curve= 0 ,0
Exp/Cntr(USF)=0,0
Exp/Cntr=0.5,0.3

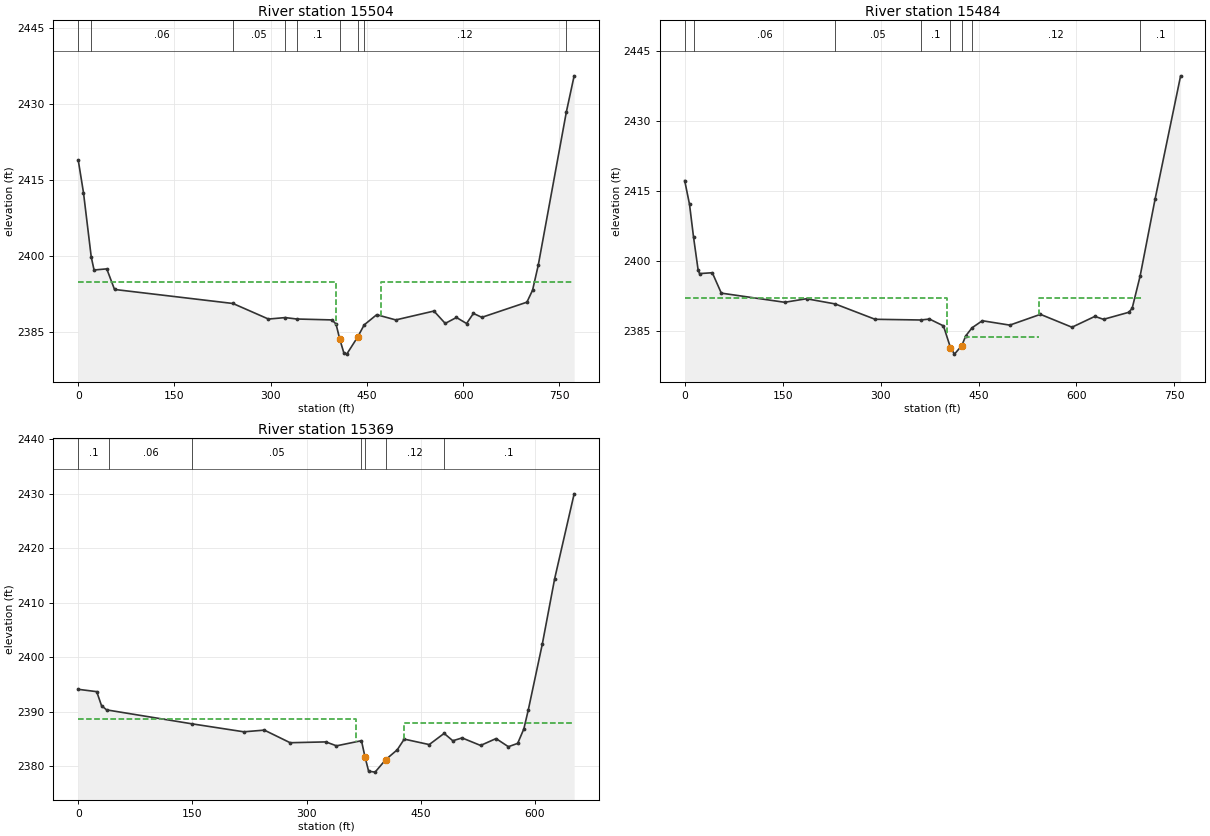
Type RM Length L Ch R = 1 ,15504   ,19.7,19.8,21.5
XS GIS Cut Line= 4
2243637.68617067425829.5130745462243998.13064183425667.636576617
2244144.07033782425616.0335901912244347.25709687425707.951409763
#Sta/Elev= 30
       0    2419     8.2 2412.56    20.3 2399.86    24.7 2397.29    44.5 2397.51
    56.6 2393.45   241.2 2390.68   296.5 2387.61   322.7  2387.9   340.4 2387.62
   395.5 2387.44   401.8 2386.63   407.6 2383.66   414.1 2380.89   418.5 2380.69
   435.5 2384.06   445.7 2386.46   465.2 2388.47   494.9 2387.44   554.4 2389.19
     572 2386.75   589.5 2387.92   605.3 2386.73   615.9 2388.72   629.1 2387.95
   699.3 2390.94   708.1  2393.3   716.9 2398.18   760.8 2428.49772.9305  2435.6
#Mann= 9 ,-1,0
       0      .1       0    20.3     .06       0   241.2     .05       0
   322.7     .08       0   340.4      .1       0   407.6    .045       0
   435.5      .1       0   445.7     .12       0   760.8      .1       0
#XS Ineff= 3 ,-1
       0     402    2395     440     472  2384.5     472 771.051    2395
Permanent Ineff=
       F       F       F
Bank Sta=407.6,435.5
XS Rating Curve= 0 ,0
Exp/Cntr(USF)=0,0
Exp/Cntr=0.5,0.3

Type RM Length L Ch R = 1 ,15484   ,118,114.5,110.4
XS GIS Cut Line= 5
 2243645.4501233425844.4244113882244002.18698812425686.883899703
2244066.12563941425664.8429079942244141.37272799425638.390902597
2244343.82529336425729.823267346
#Sta/Elev= 30
       0 2417.21     7.4 2412.13    13.6 2405.07    20.5 2398.16    22.7 2397.29
    42.3 2397.48    56.1 2393.11   153.2 2391.15   186.6 2391.91   230.4  2390.8
   291.6 2387.51   361.5 2387.36   374.9 2387.56   396.3  2386.1406.98792381.458
   413.2 2380.05   424.3 2381.87   430.6 2383.99   440.1 2385.69   455.8  2387.2
   497.9 2386.26   544.8 2388.57   593.1 2385.81   628.2 2388.13   641.4  2387.5
   680.2 2389.01   685.3 2389.87   697.5 2396.78   720.4 2413.25   759.5 2439.64
#Mann= 8 ,-1,0
       0      .1       0    13.6     .06       0   230.4     .05       0
   361.5      .1       0406.9879    .045       0   424.3      .1       0
   440.1     .12       0   697.5      .1       0
#XS Ineff= 3 ,-1
       0     401    2392     429     542  2383.7     542     700    2392
Permanent Ineff=
       F       F       F
Bank Sta=406.9879,424.3
XS Rating Curve= 0 ,0
Exp/Cntr=0.5,0.3

Type RM Length L Ch R = 1 ,15369   ,233.7,235,236.4
XS GIS Cut Line= 4
2243717.77506558425954.7785499642243941.13536714425861.385207499
2244144.90265979425737.2961510772244313.40253641425765.379463847
#Sta/Elev= 30
       0 2394.13    24.3  2393.7    30.6 2391.14    37.3 2390.36     150 2387.79
   217.6 2386.34   244.5 2386.65   278.4 2384.34   325.3 2384.49   339.3 2383.77
   372.1 2384.71   376.8 2381.71   381.5 2379.12     390 2378.95     404 2381.25
   419.1 2383.04   428.3    2385   461.1    2384   480.7 2386.05   492.1  2384.7
   504.3 2385.22   528.6 2383.84   548.9  2385.1   565.1 2383.61   577.3 2384.22
   585.4 2386.87   591.2 2390.32   609.7 2402.44   625.9 2414.41 651.501 2429.96
#Mann= 7 ,-1,0
       0      .1       0      40     .06       0     150     .05       0
   372.1     .12       0   376.8    .045       0     404     .12       0
  480.68      .1       0
#XS Ineff= 2 , 0
          365.02 2388.72  428.16         2387.87
Permanent Ineff=
       F       F
Bank Sta=376.8,404
XS Rating Curve= 0 ,0
Exp/Cntr(USF)=0,0
Exp/Cntr=0.3,0.1