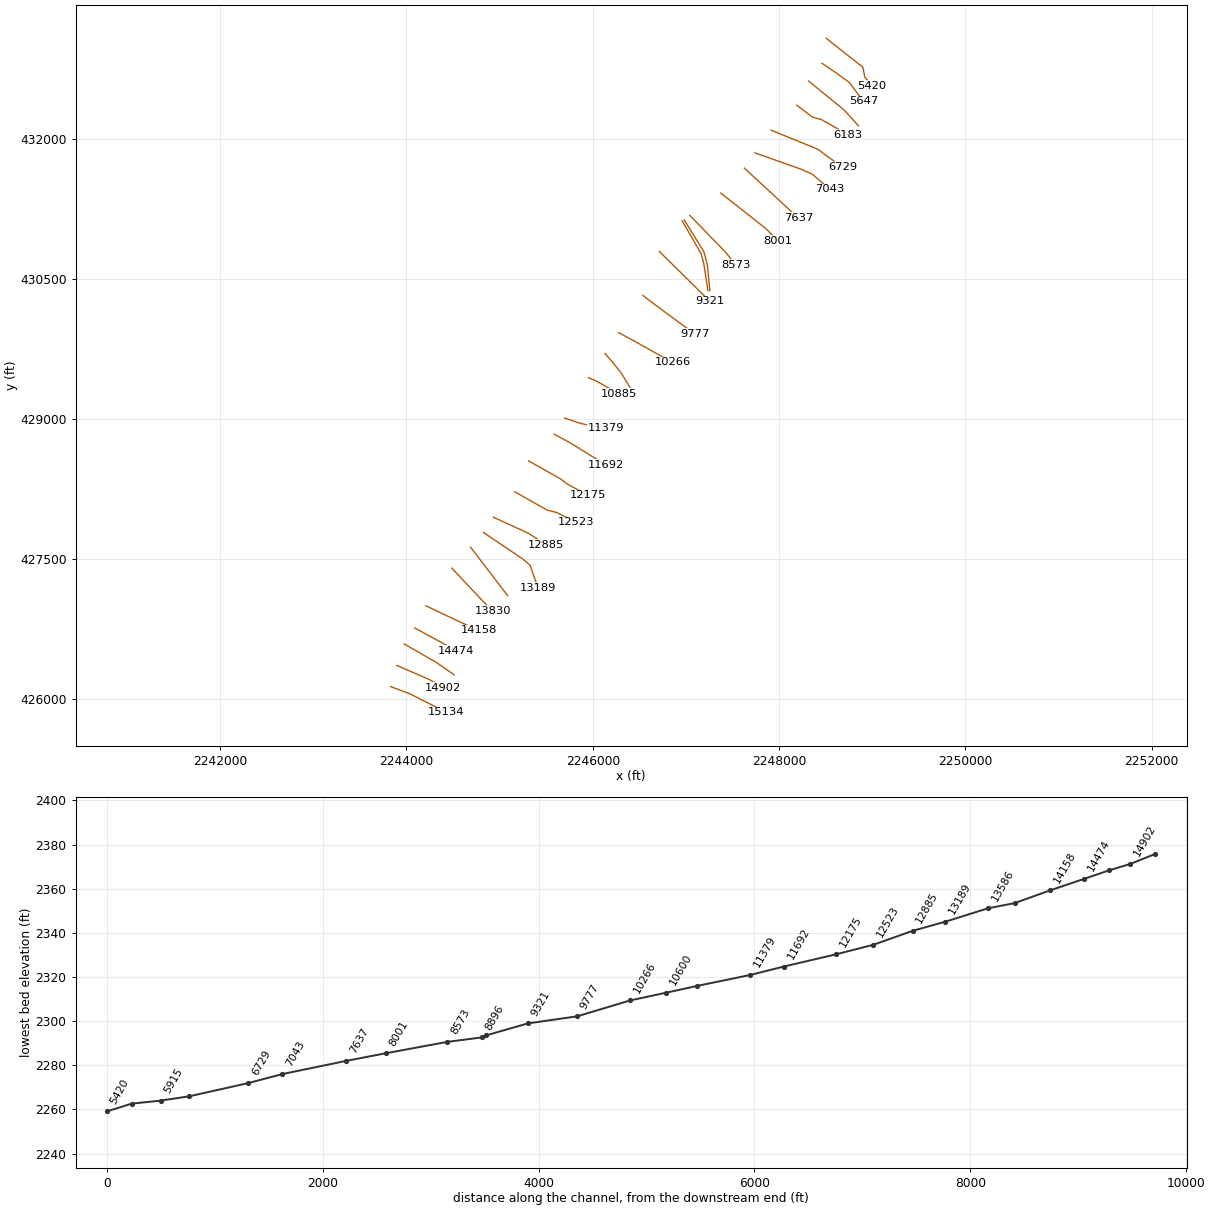
HEC-RAS study CMMNGSCK.prj: CMMNGSCK

--- CMMNGSCK.g01 (geometry) --- (continued)

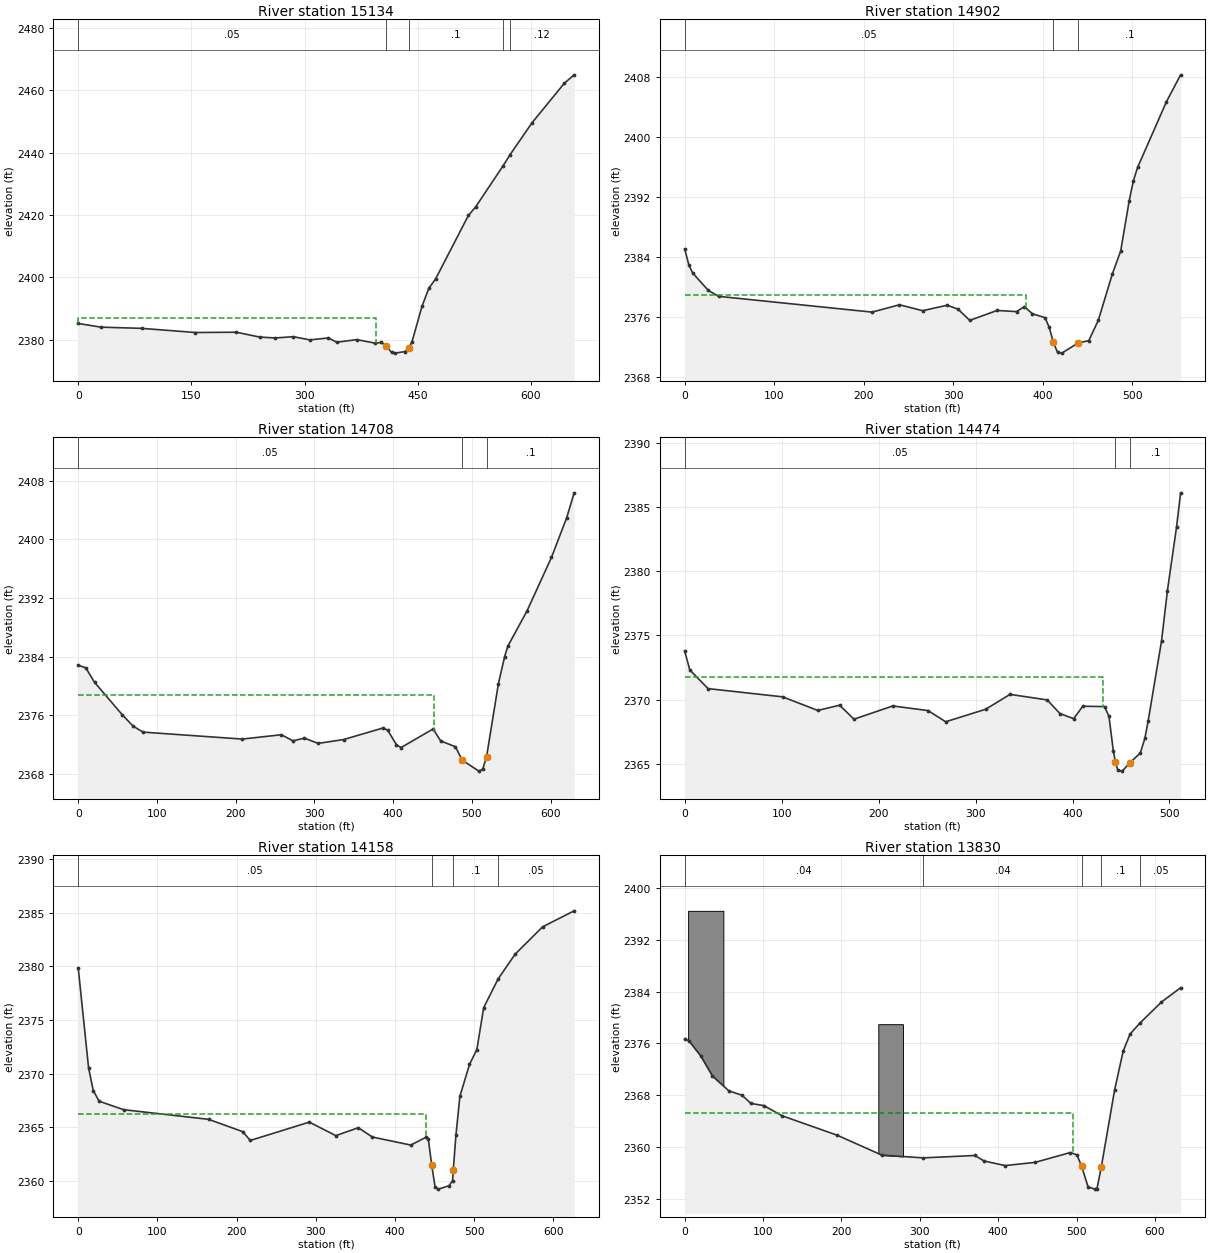
Type RM Length L Ch R = 1 ,15134   ,234.4,232.2,227.8
XS GIS Cut Line= 3
2243827.95897075426128.972848643 2244035.8349102426050.784293617
2244423.84069937425853.710618306
#Sta/Elev= 30
       0 2385.25    30.1 2384.08    83.9 2383.69   155.3 2382.36   209.6 2382.45
   240.4  2380.9     261 2380.61   285.3 2381.02   306.8 2379.99   331.6 2380.61
   342.6 2379.25   369.3 2380.08   393.1 2378.96   401.9 2379.16     408 2377.99
   415.4 2375.97   419.9 2375.75   433.3 2376.27     438 2377.38   442.3 2379.34
   455.6 2390.72   464.7 2396.56   473.7 2399.56   517.1 2419.87     527 2422.72
   562.7 2435.65   572.4 2439.39   601.4 2449.57   644.2 2462.25657.2798 2464.96
#Mann= 5 ,-1,0
       0     .05       0     408    .045       0     438      .1       0
   562.7      .1       0   572.4     .12       0
#XS Ineff= 2 , 0
          395.05 2387.02
Permanent Ineff=
       F       F
Bank Sta=408,438
XS Rating Curve= 0 ,0
Exp/Cntr(USF)=0,0
Exp/Cntr=0.3,0.1

Type RM Length L Ch R = 1 ,14902   ,195.2,194,190.8
XS GIS Cut Line= 3
2243896.07144665   426355.1290322244249.39870731426201.650462215
2244393.08077264426112.828821828
#Sta/Elev= 30
       0 2385.07     4.6 2382.97     8.8 2381.89    26.3 2379.56      38 2378.76
   209.4 2376.66     240 2377.64   265.9 2376.85   293.4 2377.58   305.4 2377.06
   318.5 2375.56     349 2376.88   370.8 2376.73   379.5 2377.39   388.5 2376.45
   402.6 2375.92   407.3 2374.64     412 2372.62   416.6 2371.32   421.4  2371.2
   439.9 2372.57   451.5 2372.86   462.2 2375.58   477.8 2381.72   487.2 2384.81
   496.6 2391.44   501.3 2394.13   506.1 2395.94   538.3 2404.68554.1414 2408.26
#Mann= 3 ,-1,0
       0     .05       0     412    .045       0   439.9      .1       0
#XS Ineff= 2 , 0
          381.52 2378.94
Permanent Ineff=
       F       F
Bank Sta=412,439.9
XS Rating Curve= 0 ,0
Exp/Cntr(USF)=0,0
Exp/Cntr=0.3,0.1

Type RM Length L Ch R = 1 ,14708   ,226,234.5,230.5
XS GIS Cut Line= 3
2243975.74968288426585.0203365292244312.09633581426392.355748926
2244511.94502668426255.204686565
#Sta/Elev= 30
       0 2382.82     9.7 2382.45    20.7 2380.49    55.9 2376.06    69.6 2374.51
    82.3 2373.68   208.3 2372.73   258.1 2373.32   272.8 2372.49   287.4 2372.86
   304.7 2372.14     337 2372.66   387.1 2374.24   393.2 2373.94   404.3 2371.94
   410.1 2371.57   450.8 2374.11   460.5 2372.47   479.1 2371.69   487.8 2369.85
     509 2368.35   513.7  2368.6   518.7 2370.29   533.8  2380.3   541.7 2383.99
   545.7 2385.41     570 2390.21   601.2 2397.55   620.6 2402.99630.0031 2406.37
#Mann= 3 ,-1,0
       0     .05       0   487.8    .045       0   518.7      .1       0
#XS Ineff= 2 , 0
          452.04 2378.79
Permanent Ineff=
       F       F
Bank Sta=487.8,518.7
XS Rating Curve= 0 ,0
Exp/Cntr(USF)=0,0
Exp/Cntr=0.3,0.1

Type RM Length L Ch R = 1 ,14474   ,309.3,315.9,306.7
XS GIS Cut Line= 3
     2244087.499      426757.156     2244484.655      426541.797
 2244535.7746939426511.029670675
#Sta/Elev= 30
       0 2373.78     5.3 2372.31    24.1 2370.86   100.9 2370.22   137.3 2369.16
   159.8 2369.57   174.6 2368.48   214.6 2369.51     251 2369.15   269.2 2368.28
   310.3 2369.25   335.6 2370.41   373.9 2369.98     387 2368.92   401.2 2368.52
   410.6 2369.49     433 2369.46   437.6  2368.7   442.1 2366.01   444.32365.152
   446.7 2364.53   451.2 2364.44459.29992365.098   469.9 2365.85   474.6 2366.98
   478.1 2368.37   491.8 2374.56   497.9 2378.49   507.3 2383.43   511.5 2386.09
#Mann= 3 ,-1,0
       0     .05       0   444.3    .045       0459.2999      .1       0
#XS Ineff= 2 , 0
        431.7201 2371.76
Permanent Ineff=
       F       F
Bank Sta=444.3,459.2999
XS Rating Curve= 0 ,0
Exp/Cntr=0.3,0.1

Type RM Length L Ch R = 1 ,14158   ,338.4,327.6,315.5
XS GIS Cut Line= 6
2244208.29427055426994.6054879162244580.32762582426818.661915569
2244673.00019446426777.0264137162244688.01739124426769.277394338
 2244769.2993695426735.0228463562244776.35204956426730.866048978
#Sta/Elev= 30
       0 2379.86    13.1 2370.53      19 2368.42    26.4 2367.42    57.4 2366.63
   164.7 2365.73   207.8 2364.58   217.3 2363.76   291.9 2365.47   325.4 2364.21
   353.8 2364.95   371.5 2364.08   420.1 2363.33   439.8 2364.08   442.1 2363.93
   446.5 2361.46   450.8 2359.41   454.9 2359.22   468.4 2359.54   472.8 2360.01
   473.7 2360.98   477.1 2364.26   482.1 2367.88   494.2 2370.85   503.5 2372.24
   512.2 2376.16   530.3 2378.82   551.9 2381.14   586.6 2383.69   626.4 2385.18
#Mann= 4 ,-1,0
       0     .05       0   446.5    .045       0   473.7      .1       0
   530.3     .05       0
#XS Ineff= 2 , 0
             439 2366.27
Permanent Ineff=
       F       F
Bank Sta=446.5,473.7
XS Rating Curve= 0 ,0
Exp/Cntr(USF)=0,0
Exp/Cntr=0.3,0.1

Type RM Length L Ch R = 1 ,13830   ,246.5,244.3,241.7
XS GIS Cut Line= 4
2244486.31197647427398.8727801032244809.99442636427055.044119638
2244865.09598673427000.3504468222244926.13441495426944.129401081
#Sta/Elev= 30
       0 2376.69     5.3 2376.38    20.2 2374.09    35.3 2370.96    56.3 2368.65
    73.3 2367.96    84.4 2366.71   101.2 2366.36   124.2  2364.8   194.6 2361.79
   251.5 2358.72   304.5 2358.29   370.4 2358.66     382 2357.81   408.9  2357.1
   447.3  2357.6   492.2 2359.12   500.5 2358.75  506.45 2357.01   514.7 2353.81
   523.2 2353.46     526  2353.5   531.6 2356.87   531.6 2356.88   548.6 2368.79
   559.5  2374.8   568.4 2377.45   581.2 2379.16   608.4 2382.38   632.8 2384.58
#Mann= 5 ,-1,0
       0     .04       0   304.5     .04       0  506.45    .045       0
   531.6      .1       0   581.2     .05       0
#XS Ineff= 2 , 0
             495 2365.24
Permanent Ineff=
       F       F
#Block Obstruct= 2 ,-1
    4.39   49.35 2396.47  247.04  278.48 2378.95
Bank Sta=506.45,531.6
XS Rating Curve= 0 ,0
Exp/Cntr(USF)=0,0
Exp/Cntr=0.3,0.1

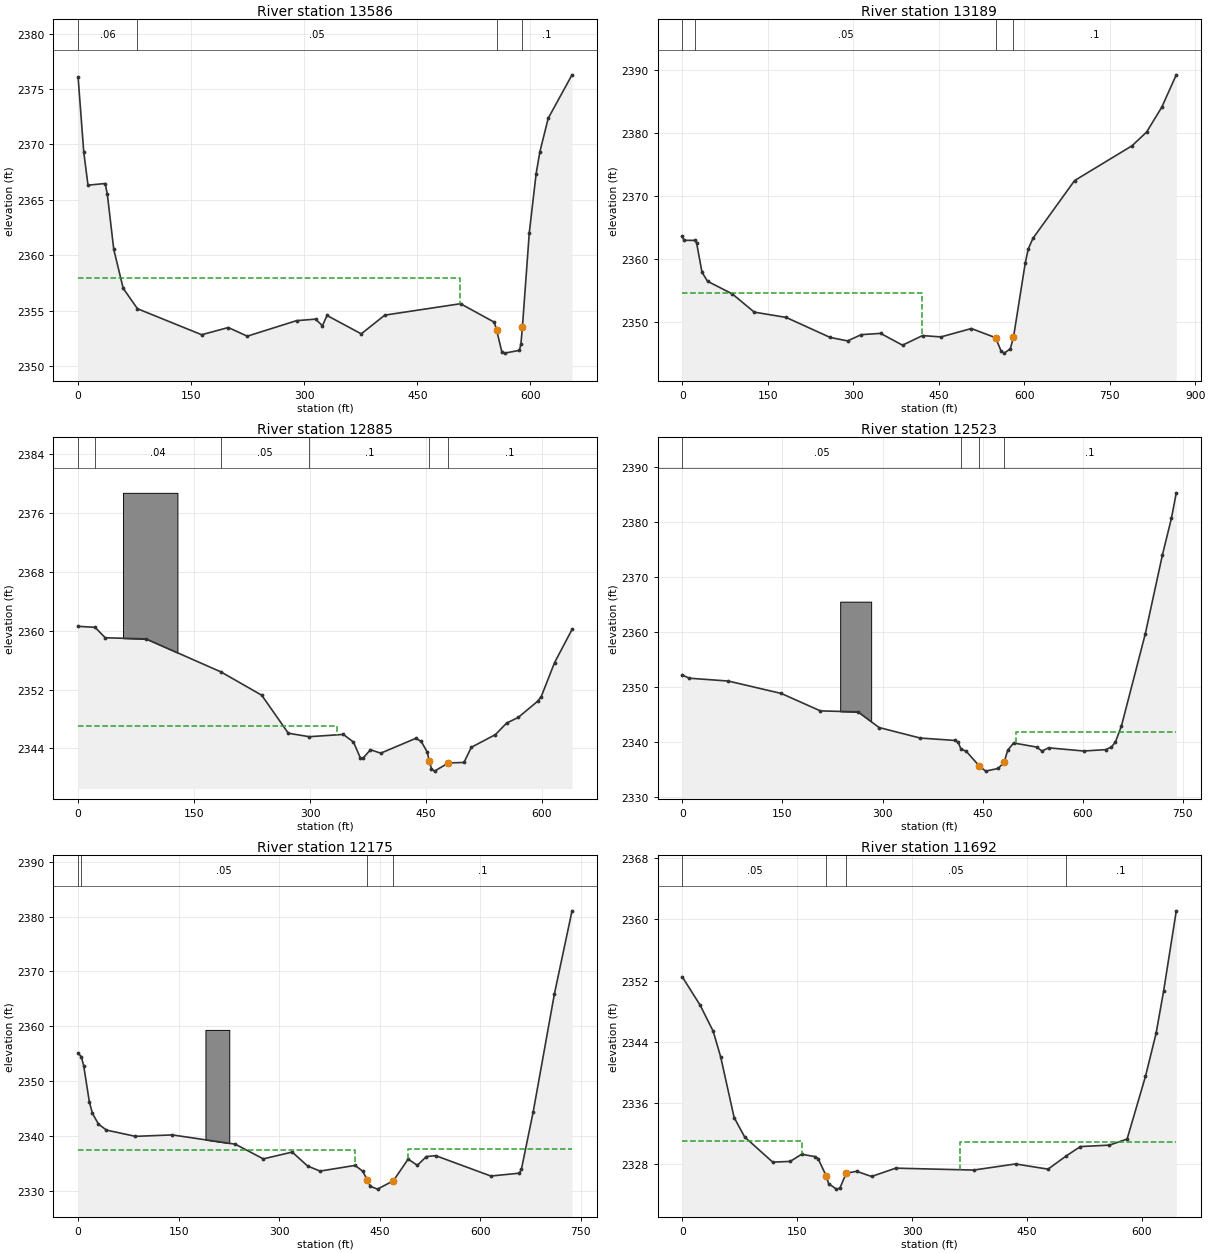
Type RM Length L Ch R = 1 ,13586   ,396.5,396.7,400.5
XS GIS Cut Line= 2
2244687.77408221427623.1672578272245086.66905158427103.395025016
#Sta/Elev= 30
       0 2376.05     7.5 2369.31    13.1 2366.32    35.9 2366.47    38.8 2365.48
    47.3 2360.52    59.8 2357.01    78.7 2355.17   163.9 2352.82   199.2 2353.47
   224.4 2352.69   289.7 2354.09   315.1 2354.23   324.1 2353.63   330.2 2354.56
   375.6  2352.9   406.8 2354.59   507.3 2355.62   552.1 2353.95   555.1 2353.25
   562.2 2351.24   565.7 2351.16   585.4 2351.41   587.4 2351.99   589.4 2353.54
   598.5 2362.03   607.6 2367.37   612.6 2369.35   623.6 2372.36655.1949 2376.28
#Mann= 4 ,-1,0
       0     .06       0    78.7     .05       0   555.1    .045       0
   589.4      .1       0
#XS Ineff= 2 , 0
             506 2357.98
Permanent Ineff=
       F       F
Bank Sta=555.1,589.4
XS Rating Curve= 0 ,0
Exp/Cntr(USF)=0,0
Exp/Cntr=0.3,0.1

Type RM Length L Ch R = 1 ,13189   ,289.1,304.2,299.2
XS GIS Cut Line= 4
2244827.45447552427780.3077003052245245.15257476427499.603832973
2245325.73741706427431.1067170212245411.69458217427188.009109427
#Sta/Elev= 30
       0  2363.6     2.8 2362.96    22.9 2362.94      25 2362.53    34.5 2357.89
    44.2 2356.46    87.6 2354.46   126.2 2351.57   182.2 2350.73   259.3 2347.56
     290 2347.01     314    2348   347.9  2348.2   386.4 2346.33   421.5 2347.85
   453.9 2347.64   507.2 2348.97   549.7 2347.52   559.7 2345.34     565 2345.07
   575.5 2345.75   581.1 2347.56   601.7 2359.29     607 2361.56   615.3 2363.27
   688.3 2372.42   789.3 2377.95   814.7 2380.11   841.3 2384.04866.8656 2389.19
#Mann= 4 ,-1,0
       0    .016       0    22.9     .05       0   549.7    .045       0
   581.1      .1       0
#XS Ineff= 2 , 0
             420 2354.63
Permanent Ineff=
       F       F
Bank Sta=549.7,581.1
XS Rating Curve= 0 ,0
Exp/Cntr(USF)=0,0
Exp/Cntr=0.3,0.1

Type RM Length L Ch R = 1 ,12885   ,333.5,362.1,361.6
XS GIS Cut Line= 3
2244932.21477051427945.5066270122245308.27736789 427773.59229678
2245497.65174729427651.371952631
#Sta/Elev= 30
       0 2360.59    21.9 2360.46    35.1 2359.04    87.9 2358.88   184.7  2354.4
   237.5 2351.23   271.9 2346.06     299 2345.59     343  2345.9   356.2 2344.86
     365 2342.73   368.5 2342.67   378.2 2343.82   391.4 2343.35   436.9 2345.37
   443.8 2344.95   451.5 2343.52   454.2 2342.31   457.1 2341.21     461 2340.91
   478.9 2342.02   499.1 2342.09   508.6 2344.15   539.7 2345.87   554.4 2347.45
   569.2  2348.2   594.3  2350.4     599 2351.03   616.3 2355.66 638.884 2360.17
#Mann= 6 ,-1,0
       0    .016       0    21.9     .04       0   184.7     .05       0
     299      .1       0   454.2    .045       0   478.9      .1       0
#XS Ineff= 2 , 0
          334.42 2347.07
Permanent Ineff=
       F       F
#Block Obstruct= 1 ,-1
   58.12  128.45 2378.74
Bank Sta=454.2,478.9
XS Rating Curve= 0 ,0
Exp/Cntr(USF)=0,0
Exp/Cntr=0.3,0.1

Type RM Length L Ch R = 1 ,12523   ,358.2,348.3,322.7
XS GIS Cut Line= 4
2245163.22465176428218.1520101152245508.39639293428022.062227194
2245614.49976862427995.2006130952245822.67727788427889.097237405
#Sta/Elev= 30
       0  2352.1    10.3 2351.53    68.9 2351.01   148.3 2348.75   206.8 2345.58
   263.3  2345.4   294.8 2342.55   356.4 2340.64   409.1  2340.2   413.3 2339.84
   417.4 2338.67   425.6  2338.2   445.2 2335.52   454.5 2334.62   473.3 2335.11
   482.1 2336.24   487.5 2338.41   496.3 2339.74   530.8    2339   538.9 2338.27
   548.7 2338.86   601.4 2338.28   634.1 2338.53     643    2339     649 2339.95
   657.9 2342.83   693.6 2359.57   719.3 2373.95   732.8 2380.62740.0903 2385.26
#Mann= 4 ,-1,0
       0     .05       0   417.4      .1       0   445.2    .045       0
   482.1      .1       0
#XS Ineff= 2 , 0
                          499.38         2341.68
Permanent Ineff=
       F       F
#Block Obstruct= 1 ,-1
   236.5  282.91 2365.46
Bank Sta=445.2,482.1
XS Rating Curve= 0 ,0
Exp/Cntr(USF)=0,0
Exp/Cntr=0.3,0.1

Type RM Length L Ch R = 1 ,12175   ,425.6,482.4,395.5
XS GIS Cut Line= 4
 2245309.6204486428549.8929442352245652.10602836428357.832403429
2245724.63238642428302.7660945262245946.24070274428180.545750377
#Sta/Elev= 30
       0 2355.06     4.8 2354.42     8.3  2352.8    16.7 2346.23    21.3  2344.1
    30.4 2342.13    42.3 2341.04    85.5  2339.9   140.5 2340.16   234.5 2338.47
   276.3 2335.79   319.4 2337.03   342.3 2334.49   360.9 2333.56   413.2  2334.6
   424.6 2333.53   431.3 2331.95     436 2330.78   446.7 2330.27   470.3  2331.8
   492.3 2335.74     506 2334.62   519.7 2336.22   533.5 2336.37   615.7 2332.66
   658.3 2333.18   661.4 2333.96   678.9 2344.39   710.6 2365.94736.8019 2381.04
#Mann= 4 ,-1,0
       0    .016       0     4.8     .05       0   431.3    .045       0
   470.3      .1       0
#XS Ineff= 2 , 0
          412.39 2337.46  492.17         2337.54
Permanent Ineff=
       F       F
#Block Obstruct= 1 ,-1
  189.95  225.49 2359.32
Bank Sta=431.3,470.3
XS Rating Curve= 0 ,0
Exp/Cntr(USF)=0,0
Exp/Cntr=0.3,0.1

Type RM Length L Ch R = 1 ,11692   ,244.4,313.4,291.9
XS GIS Cut Line= 3
2245584.95199311428837.3122150912245782.38485674428728.522677991
2246138.30124355428506.914361677
#Sta/Elev= 30
       0 2352.47    23.1  2348.8    40.2 2345.39      50 2342.03    67.6  2334.1
    81.3 2331.57   117.9 2328.28   140.7 2328.37   155.6  2329.3   172.7 2329.01
   177.2 2328.73     188 2326.43   190.9 2325.47   201.1 2324.75   205.6 2324.88
   213.8 2326.82   227.5 2327.08   246.9  2326.4   278.5 2327.49   380.2 2327.24
   434.9 2328.04   477.3 2327.36   500.8 2329.07   519.5 2330.31   557.4  2330.5
   580.5 2331.29   604.5 2339.49   618.3 2345.09   628.1 2350.59644.6909 2361.11
#Mann= 4 ,-1,0
       0     .05       0     188    .045       0   213.8     .05       0
   500.8      .1       0
#XS Ineff= 2 , 0
          155.77 2331.02  362.03         2330.97
Permanent Ineff=
       F       F
Bank Sta=188,213.8
XS Rating Curve= 0 ,0
Exp/Cntr(USF)=0,0
Exp/Cntr=0.3,0.1

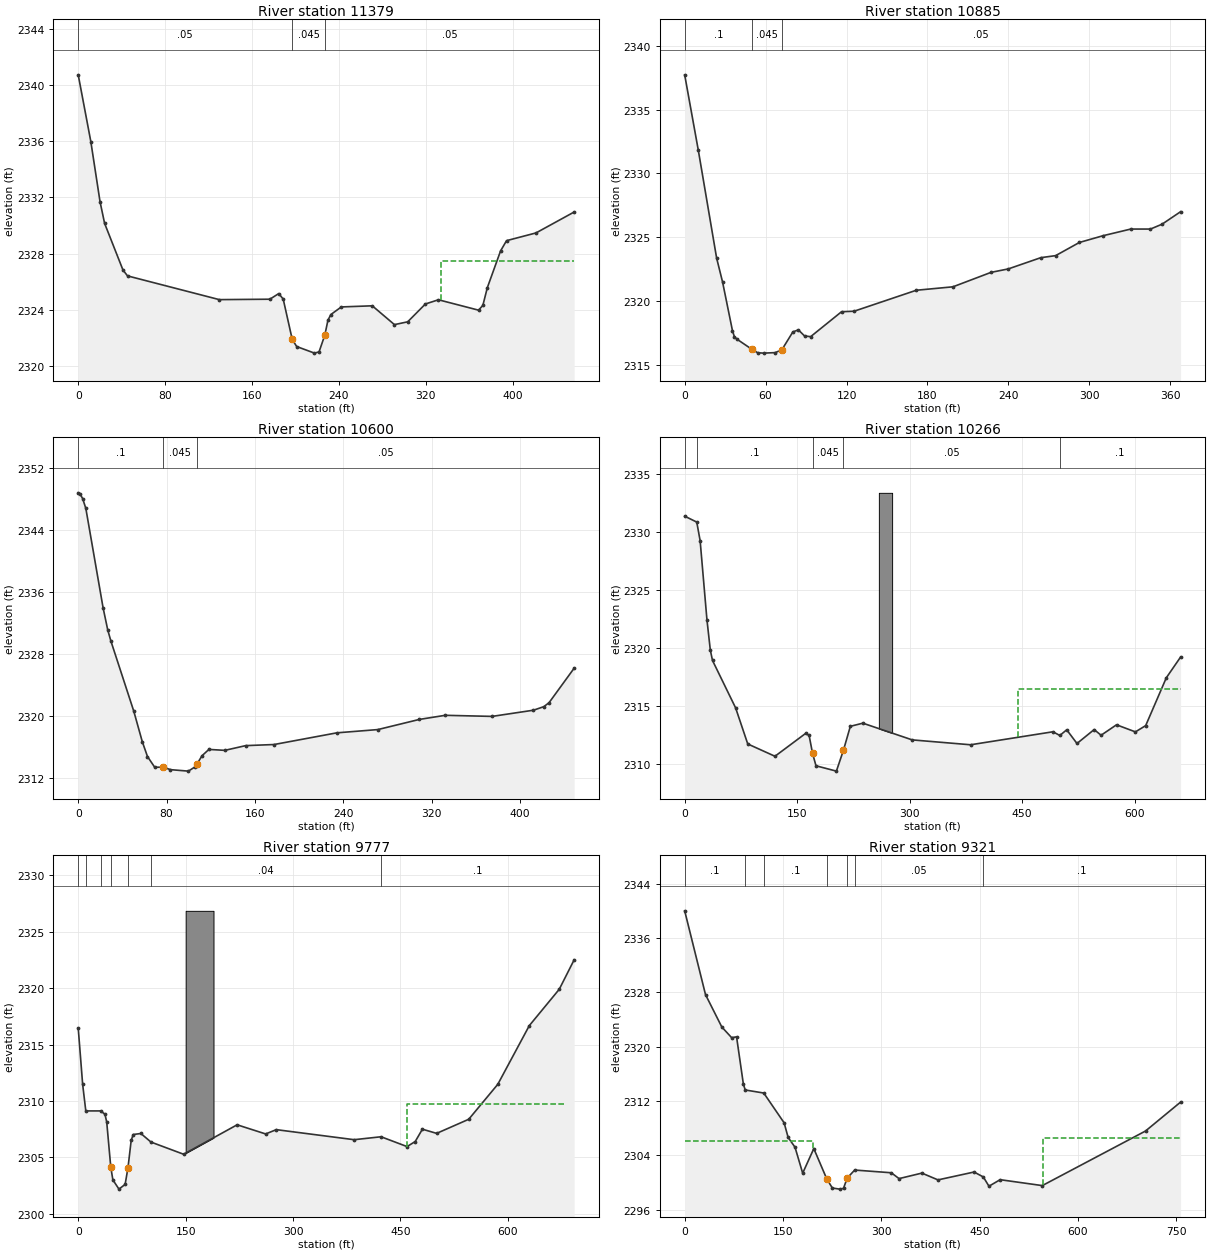
Type RM Length L Ch R = 1 ,11379   ,492.8,493.3,477.1
XS GIS Cut Line= 4
2245697.14492618429009.8219079422245862.39163224428953.651090863
2245923.78764161 428938.628663042246138.67367439428897.480273784
#Sta/Elev= 30
       0 2340.73    11.6 2335.98    20.1 2331.69    24.3 2330.15    41.2 2326.83
    45.4 2326.41   129.9 2324.72   176.4 2324.75   184.6 2325.15   188.7 2324.76
     197 2321.89   201.1 2321.38   217.5 2320.91   221.7    2321     227 2322.19
   229.9 2323.26   232.6 2323.66   242.2  2324.2   270.7 2324.28   291.1 2322.94
   303.3 2323.14   319.6 2324.41   331.6 2324.71   368.5 2323.97   372.5 2324.31
   376.6 2325.57   388.8 2328.19   394.3 2328.92   421.4 2329.47456.5301 2330.96
#Mann= 3 ,-1,0
       0     .05       0     197    .045       0     227     .05       0
#XS Ineff= 2 , 0
                           333.8         2327.44
Permanent Ineff=
       F       F
Bank Sta=197,227
XS Rating Curve= 0 ,0
Exp/Cntr(USF)=0,0
Exp/Cntr=0.3,0.1

Type RM Length L Ch R = 1 ,10885   ,292.4,285.2,253.2
XS GIS Cut Line= 3
2245954.29918697429441.6985323142246040.25635208 429405.43535328
2246277.98163686429268.441121377
#Sta/Elev= 30
       0 2337.72    10.1 2331.82    23.7 2323.37    28.1  2321.5    35.4 2317.71
    36.8 2317.24    38.5 2317.05    49.8 2316.24    54.1 2315.97    58.5 2315.94
    67.2 2315.98    72.1 2316.21    80.2  2317.6    84.3 2317.76    88.9 2317.28
    93.4 2317.23   116.3 2319.18   125.6 2319.22   171.7 2320.86   198.9 2321.13
   227.1 2322.26   239.9 2322.53     264 2323.41     275 2323.57   292.6  2324.6
   310.2 2325.13   330.7 2325.65   345.3 2325.65   353.9 2326.03367.6667 2327.01
#Mann= 3 ,-1,0
       0      .1       0    49.8    .045       0    72.1     .05       0
Bank Sta=49.8,72.1
XS Rating Curve= 0 ,0
Exp/Cntr(USF)=0,0
Exp/Cntr=0.3,0.1

Type RM Length L Ch R = 1 ,10600   ,303.5,334.4,350
XS GIS Cut Line= 4
2246131.62102221429702.3198638572246217.00721945429601.753898224
2246300.49594564 429499.290461542246397.26696917429341.800364416
#Sta/Elev= 30
       0 2348.79     1.5 2348.69       4 2348.05     6.9 2346.78    22.5 2333.97
    26.7 2331.12    29.6 2329.66    50.3 2320.62      58 2316.69    62.7 2314.77
    69.3 2313.38    76.82313.414    83.5 2313.08    99.7 2312.89   105.9 2313.45
   107.62313.828   112.1 2314.88   118.3 2315.69   132.7 2315.57   151.6 2316.18
   177.2 2316.32   234.1 2317.83   271.2 2318.25   308.8 2319.56   332.2 2320.09
   374.6 2319.95   412.1 2320.75   421.5 2321.21   426.2 2321.72   448.9 2326.17
#Mann= 3 ,-1,0
       0      .1       0    76.8    .045       0   107.6     .05       0
Bank Sta=76.8,107.6
XS Rating Curve= 0 ,0
Exp/Cntr(USF)=0,0
Exp/Cntr=0.3,0.1

Type RM Length L Ch R = 1 ,10266   ,481,489.2,441.7
XS GIS Cut Line= 4
2246277.98163686429925.2075860922246413.63278806429852.681228025
 2246480.7868233429815.0749682872246856.84942069429605.554378316
#Sta/Elev= 30
       0 2331.34    16.1 2330.83    20.6 2329.23    29.7 2322.41    34.2  2319.8
    37.1 2318.91    67.9 2314.83    84.1 2311.72   120.4 2310.66   161.3 2312.63
   165.9 2312.46   170.5 2310.91   175.1 2309.84   202.3 2309.38   211.7 2311.18
   220.9 2313.24   237.6 2313.51   303.4 2312.07   381.2 2311.65   491.1 2312.77
   500.2 2312.45   509.4 2312.94   523.1 2311.76     546 2312.96   555.2 2312.47
   575.8 2313.37     601 2312.76   614.7  2313.3   642.2 2317.42661.2795 2319.21
#Mann= 5 ,-1,0
       0    .016       0    16.1      .1       0   170.5    .045       0
   211.7     .05       0   500.2      .1       0
#XS Ineff= 2 , 0
                          444.19         2316.49
Permanent Ineff=
       F       F
#Block Obstruct= 1 ,-1
  258.91  276.61 2333.35
Bank Sta=170.5,211.7
XS Rating Curve= 0 ,0
Exp/Cntr(USF)=0,0
Exp/Cntr=0.3,0.1

Type RM Length L Ch R = 1 ,9777    ,457.8,456,437.3
XS GIS Cut Line= 3
2246539.30869085430324.2676860772246604.35024816430273.065488671
2247094.57470546429910.433698337
#Sta/Elev= 30
       0 2316.47     6.2 2311.47    10.6 2309.12    31.3 2309.12    37.3 2308.83
    39.8 2308.14    45.5 2304.12    48.4 2303.01    56.9 2302.19    65.5 2302.61
   69.482304.074      74 2306.52    76.9 2307.03    87.5 2307.12   101.6 2306.36
   147.2 2305.28   221.9 2307.89   261.7 2307.08   276.6 2307.46   385.3 2306.57
   422.9 2306.83   459.2 2305.96   470.6 2306.41   480.6  2307.5   500.5 2307.13
   545.3 2308.38   585.9 2311.48   629.9 2316.68   671.7  2319.9   692.5 2322.51
#Mann= 7 ,-1,0
       0      .1       0    10.6    .016       0    31.3     .08       0
    45.5    .045       0   69.48    .016       0   101.6     .04       0
   422.9      .1       0
#XS Ineff= 1 ,-1
   458.9  678.852309.757
Permanent Ineff=
       F
#Block Obstruct= 1 ,-1
  150.02  188.91 2326.85
Bank Sta=45.5,69.48
XS Rating Curve= 0 ,0
Exp/Cntr(USF)=0,0
Exp/Cntr=0.3,0.1

Type RM Length L Ch R = 1 ,9321    ,342.3,390.6,211.4
XS GIS Cut Line= 2
2246715.82594667430795.5238828922247254.40130935430263.663923736
#Sta/Elev= 30
       0 2339.98    31.8 2327.64    56.7 2322.87    71.6 2321.31    79.2 2321.42
    89.6 2314.46    92.4  2313.6   120.7 2313.15   151.8 2308.76   157.9 2306.61
   168.4 2305.17   180.1 2301.35   197.1 2304.97   216.9 2300.49   225.4 2299.16
   236.7    2299   242.4 2299.11     248 2300.63   259.5 2301.81   315.3 2301.41
   327.2 2300.55     362 2301.36   386.6 2300.36   441.7 2301.52   455.8 2300.79
   464.4 2299.43   481.5 2300.39   545.8 2299.52   703.4 2307.56756.9269 2311.82
#Mann= 7 ,-1,0
       0      .1       0    92.4    .016       0   120.7      .1       0
   216.9    .045       0     248    .016       0   259.5     .05       0
   455.8      .1       0
#XS Ineff= 2 , 0
          196.06 2306.02  546.18         2306.59
Permanent Ineff=
       F       F
Bank Sta=216.9,248
XS Rating Curve= 0 ,0
Exp/Cntr(USF)=0,0
Exp/Cntr=0.5,0.3

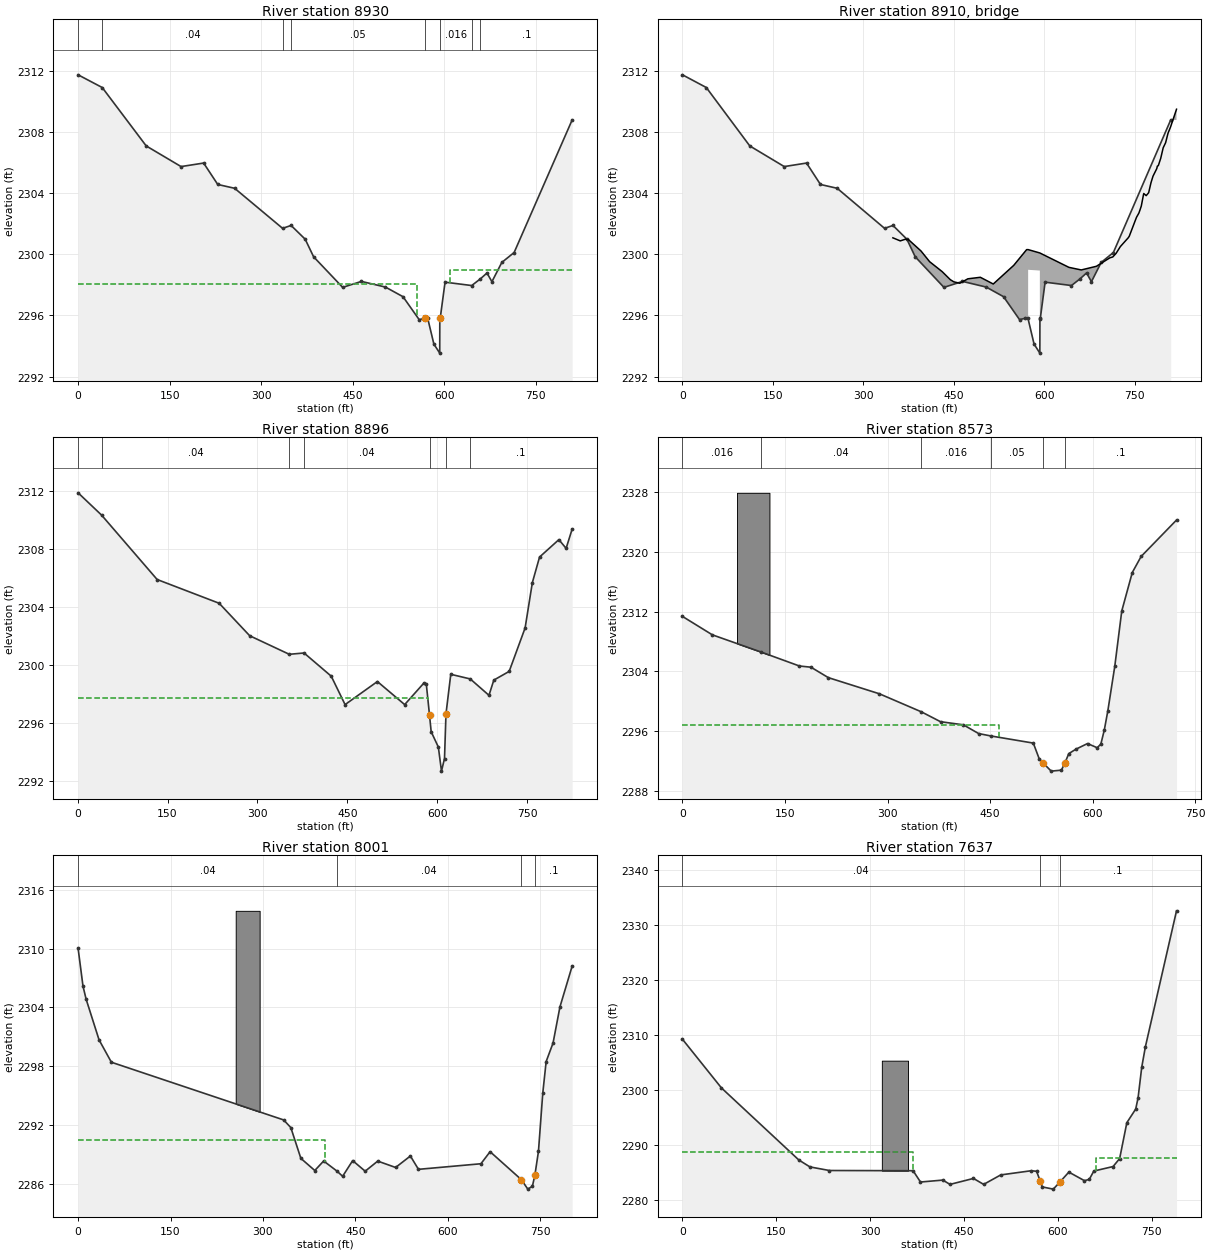
Type RM Length L Ch R = 1 ,8930    ,34.4,34.1,31.1
BEGIN DESCRIPTION:
Channel burn based on survey CUM032BU
END DESCRIPTION:
XS GIS Cut Line= 5
2246960.26663497431123.2355748962247163.07182141430772.691510908
2247191.27651622430666.5881352172247204.70732327430583.317131511
2247235.59817948430375.139622246
#Sta/Elev= 30
       0 2311.73    39.5  2310.9   111.6 2307.08   168.7 2305.73   205.7 2305.96
   228.8 2304.56   256.5 2304.31   335.1 2301.69     349 2301.88   372.1 2300.98
   385.9 2299.83   433.5 2297.83   464.3 2298.22   503.6 2297.85   532.4 2297.22
   558.9 2295.72   568.5 2295.81   572.9  2295.8     583 2294.12  592.58 2293.53
   592.7 2295.74   593.5 2295.85   601.3 2298.17     645 2297.95   659.3 2298.39
     670 2298.77   678.1  2298.2   694.3 2299.46   714.5 2300.11809.5751 2308.78
#Mann= 8 ,-1,0
       0    .016       0    39.5     .04       0   335.1    .016       0
     349     .05       0   568.5    .045       0   593.5    .016       0
     645      .1       0   659.3      .1       0
#XS Ineff= 2 , 0
             556 2298.08     609         2298.97
Permanent Ineff=
       F       F
Bank Sta=568.5,593.5
XS Rating Curve= 0 ,0
Exp/Cntr(USF)=0,0
Exp/Cntr=0.5,0.3

Type RM Length L Ch R = 3 ,8910    ,,,
BEGIN DESCRIPTION:
Unnamed Road
Survey: 54075CUM030
Railing was not included
END DESCRIPTION:
Bridge Culvert--1,0,-1,-1, 0
Deck Dist Width WeirC Skew NumUp NumDn MinLoCord MaxHiCord MaxSubmerge Is_Ogee
17,10,2.6,0, 44, 39, , , 0.98, 0, 0,0,,
   348.9   361.1   370.4   375.1   395.5   409.8   430.6   444.2   450.1   459.9
   473.2   493.9   515.3  549.27  570.68  573.19  592.58  640.75   661.2   686.4
   708.5   713.5   718.9   726.1   739.3   740.9   752.8   756.8   758.6   760.8
   764.8   768.9     773   776.9   780.2   786.5   787.4     789     793   797.1
   801.1   805.1   809.3   819.2
 2301.07 2300.87 2300.99 2300.94 2300.21 2299.51 2298.86 2298.33 2298.19  2298.1
 2298.39 2298.49 2298.05 2299.27  2300.3  2300.3 2300.08 2299.14 2298.97 2299.21
 2299.76 2299.82 2300.05  2300.5 2301.08 2301.18 2302.41 2302.69 2302.89 2303.15
 2303.97 2303.83 2304.02 2304.68  2305.1  2305.6 2305.76 2305.79 2306.27 2306.96
 2307.29 2307.91 2308.32 2309.48
                                                                                
                                         2298.98 2298.93
                                                                                
                                                                                
                                
   389.1   395.5   409.8   430.6   444.2   450.1   459.9   473.2   493.9   518.8
   531.2   539.3  545.06  566.27  592.93     600  612.05  623.23  657.75   660.1
   686.4   716.5   726.1   740.9   752.8   756.8   758.6   760.8   764.8   768.9
     773   776.9   780.2   786.5   787.4     789     793   797.1   798.2
 2300.41 2300.21 2299.51 2298.86 2298.33 2298.19  2298.1 2298.39 2298.49 2297.98
 2298.02 2298.17 2298.48 2299.27  2300.3 2300.12 2300.08  2300.1 2299.14 2298.97
 2299.21 2299.93  2300.5 2301.18 2302.41 2302.69 2302.89 2303.15 2303.97 2303.83
 2304.02 2304.68  2305.1  2305.6 2305.76 2305.79 2306.27 2306.96 2307.06
                                                                                
                                 2298.97 2298.97 2298.97
                                                                                
                                                                        
BR Coef=-1 ,-1 , 0 ,, 0 ,,,0.8,0,1,0,
WSPro=,,,, 1 ,,,, 0 ,,,, 0 ,,,,-1 ,-1 ,-1 , 0 , 0 , 0 , 0 , 0
BR U #Sta/Elev= 30
       0 2311.73    39.5  2310.9   111.6 2307.08   168.7 2305.73   205.7 2305.96
   228.8 2304.56   256.5 2304.31   335.1 2301.69     349 2301.88   372.1 2300.98
   385.9 2299.83   433.5 2297.83   464.3 2298.22   503.6 2297.85   532.4 2297.22
   558.9 2295.72   568.5 2295.81   572.9  2295.8     583 2294.12  592.58 2293.53
   592.7 2295.74   593.5 2295.85   601.3 2298.17     645 2297.95   659.3 2298.39
     670 2298.77   678.1  2298.2   694.3 2299.46   714.5 2300.11 809.575 2308.78
BR U #Mann= 8
       0    .016    39.5     .04   335.1    .016     349     .05   568.5     .04
   593.5    .016     645      .1   659.3      .1
BR D #Sta/Elev= 30
      .9 2311.86    40.1 2310.32   132.7 2305.88   236.2 2304.24   287.1    2302
   353.1 2300.72   377.8 2300.81   423.1 2299.21   446.2 2297.25   500.1 2298.84
   545.6 2297.25   577.3 2298.72   581.7 2298.66   587.1  2296.5   589.8 2295.38
  601.78 2294.32     607 2292.66  612.05 2293.53   613.8 2296.31   621.9  2299.3
     655 2299.02   686.2 2297.89   694.3 2298.94   719.9 2299.54   746.5 2302.54
   758.6 2305.67   770.6 2307.43   802.8 2308.63   814.9 2308.03 824.954 2309.36
BR D #Mann= 6
      .9    .016    40.1     .04   353.1    .016   377.8     .04   587.1     .04
     655      .1
BC Design=,, 0 ,, 0 ,,,,,,
BC Use User HTab Curves=0
BC User HTab FreeFlow(D)= 0

Type RM Length L Ch R = 1 ,8896    ,210.1,323.3,319.7
BEGIN DESCRIPTION:
Channel burned from survey CUM028BD
END DESCRIPTION:
XS GIS Cut Line= 5
2246981.75592625431133.9802205362247191.27651622430795.523882892
2247228.88277595430659.8727316932247236.94126018430576.601727987
2247257.08747076430375.139622246
#Sta/Elev= 30
      .9 2311.86    40.1 2310.32   132.7 2305.88   236.2 2304.24   287.1    2302
   353.1 2300.72   377.8 2300.81   423.1 2299.21   446.2 2297.25   500.1 2298.84
   545.6 2297.25   577.3 2298.72   581.7 2298.66   587.1  2296.5   589.8 2295.38
  601.78 2294.32     607 2292.66  612.05 2293.53   614.5 2296.61   622.5 2299.34
     655 2299.02   686.2 2297.89   694.3 2298.94   719.9 2299.54   746.5 2302.54
   758.6 2305.67   770.6 2307.43   802.8 2308.63   814.9 2308.03824.9541 2309.36
#Mann= 7 ,-1,0
      .9    .016       0    40.1     .04       0   353.1    .016       0
   377.8     .04       0   587.1    .045       0   614.5      .1       0
     655      .1       0
#XS Ineff= 2 ,-1
      .9 584.363  2297.7 618.326 824.055  2297.7
Permanent Ineff=
       F       F
Bank Sta=587.1,614.5
XS Rating Curve= 0 ,0
Exp/Cntr(USF)=0,0
Exp/Cntr=0.5,0.3

Type RM Length L Ch R = 1 ,8573    ,519.1,571.4,537.6
XS GIS Cut Line= 4
2247040.85147726431183.6742066192247387.36629914 430827.75781981
2247443.77568875430765.9761073832247532.41901527430654.500408873
#Sta/Elev= 30
       0 2311.37    43.7  2308.9   115.1 2306.59   171.1 2304.72     188 2304.56
   213.4 2303.16   288.2 2300.99   349.6 2298.57   377.5 2297.25     411 2296.83
   433.3 2295.66     451 2295.34   513.3 2294.38   521.8  2292.3   527.3 2291.74
   539.5 2290.62   554.4 2290.75   559.8 2291.77   565.2 2292.97   575.6 2293.56
   592.6 2294.32   606.7 2293.76   612.1 2294.24   617.2 2296.15   622.3 2298.69
   632.5 2304.69   642.7  2312.1   658.1 2317.26     671 2319.41 722.822  2324.3
#Mann= 6 ,-1,0
       0    .016       0   115.1     .04       0   349.6    .016       0
     451     .05       0   527.3    .045       0   559.8      .1       0
#XS Ineff= 2 , 0
          462.42 2296.86
Permanent Ineff=
       F       F
#Block Obstruct= 1 ,-1
   79.76  127.24 2327.95
Bank Sta=527.3,559.8
XS Rating Curve= 0 ,0
Exp/Cntr(USF)=0,0
Exp/Cntr=0.3,0.1

Type RM Length L Ch R = 1 ,8001    ,330.6,364,355.3
XS GIS Cut Line= 3
2247373.93549209431422.7425720982247846.69990023 431050.70921683
2247990.40953566430911.028823516
#Sta/Elev= 30
       0 2310.01     7.9 2306.17      13 2304.83      34 2300.68      54  2298.4
   333.7 2292.51   345.3 2291.73   361.6 2288.59   384.2 2287.35   398.6 2288.32
   420.2 2287.29   429.4 2286.76   445.7 2288.36     466 2287.28   486.4 2288.31
   515.4 2287.66   539.4 2288.83   552.5 2287.47   653.9 2288.04   668.8 2289.27
   719.7 2286.41     730 2285.45   737.5 2285.75   741.5 2286.88   747.3  2289.3
   754.3 2295.24   759.8 2298.47     771 2300.36   782.2 2304.05 802.001 2308.21
#Mann= 4 ,-1,0
       0     .04       0   420.2     .04       0   719.7    .045       0
   741.5      .1       0
#XS Ineff= 2 , 0
          401.13 2290.46
Permanent Ineff=
       F       F
#Block Obstruct= 1 ,-1
  255.83  294.68 2313.85
Bank Sta=719.7,741.5
XS Rating Curve= 0 ,0
Exp/Cntr(USF)=0,0
Exp/Cntr=0.3,0.1

Type RM Length L Ch R = 1 ,7637    ,410.8,594.1,548.6
XS GIS Cut Line= 2
2247626.43466462431691.3587130852248206.64552915431155.469511815
#Sta/Elev= 30
       0 2309.23    62.3  2300.4     186 2287.32   203.8 2286.06   234.9 2285.41
   368.7 2285.37   380.5 2283.32   416.2 2283.67   427.7 2282.89   465.2 2283.97
   481.5 2282.89   508.8 2284.61   557.6 2285.37   566.1 2285.27   571.7 2283.56
   575.1 2282.43   592.8 2282.03   602.9 2283.26   617.7 2285.12   642.5 2283.57
   650.3 2283.79   657.6 2285.31   688.4 2286.13   698.9 2287.58   710.4 2294.09
   724.6 2296.57   728.4 2298.63   734.2 2304.15   740.1  2307.9 789.824 2332.55
#Mann= 3 ,-1,0
       0     .04       0   571.7    .045       0   602.9      .1       0
#XS Ineff= 2 , 0
          367.77 2288.82  661.18         2287.69
Permanent Ineff=
       F       F
#Block Obstruct= 1 ,-1
  318.71  360.58 2305.35
Bank Sta=571.7,602.9
XS Rating Curve= 0 ,0
Exp/Cntr(USF)=0,0
Exp/Cntr=0.3,0.1

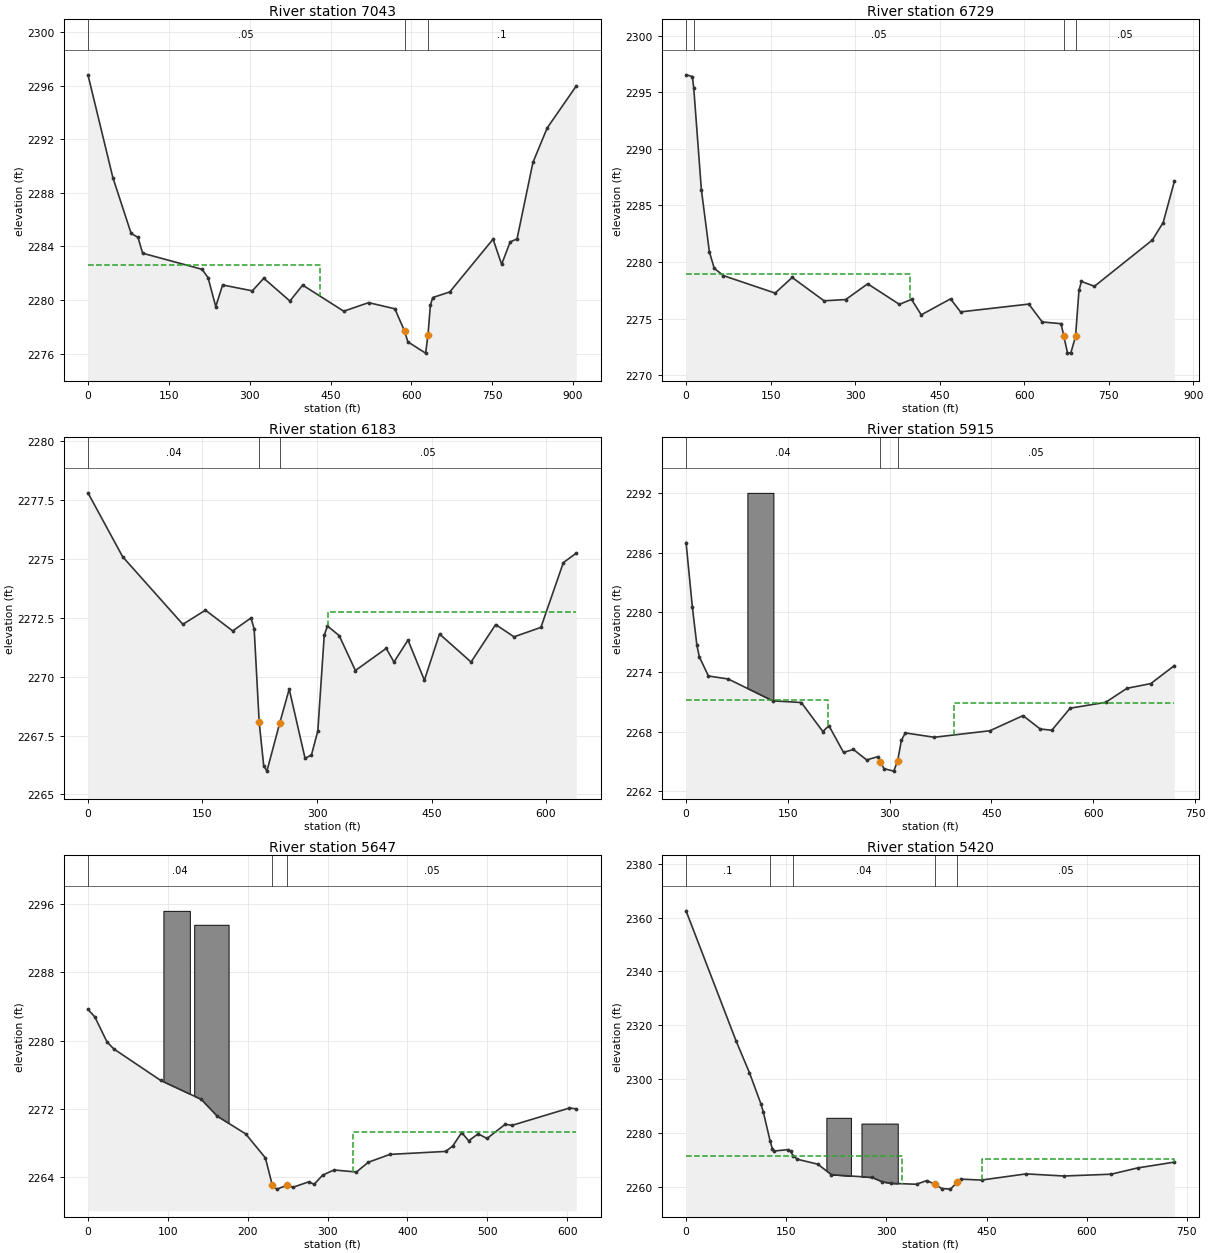
Type RM Length L Ch R = 1 ,7043    ,275.9,314.2,262.3
XS GIS Cut Line= 4
2247740.59652454431853.8714783832248242.90870818431676.584825331
2248359.75672951431622.8615971342248545.10186679431463.034993246
#Sta/Elev= 30
       0 2296.81    46.2 2289.14    80.1 2284.97    92.9 2284.67   101.4 2283.49
   211.6 2282.29   222.8 2281.67   237.1  2279.5   249.8 2281.12     305 2280.68
   326.2 2281.62   374.7 2279.92   398.3 2281.11   474.6 2279.16   520.7  2279.8
   569.4 2279.34   587.5 2277.67   593.5 2276.87   626.5 2276.03   630.9 2277.41
   635.3  2279.6   639.7 2280.18   671.3  2280.6   751.6 2284.54   767.5 2282.66
   783.3 2284.33   796.1 2284.56   825.6 2290.27     852 2292.84 906.026 2295.98
#Mann= 3 ,-1,0
       0     .05       0   587.5    .045       0   630.9      .1       0
#XS Ineff= 2 , 0
          430.29 2282.63
Permanent Ineff=
       F       F
Bank Sta=587.5,630.9
XS Rating Curve= 0 ,0
Exp/Cntr(USF)=0,0
Exp/Cntr=0.3,0.1

Type RM Length L Ch R = 1 ,6729    ,387.1,545.8,486
XS GIS Cut Line= 4
2247913.85393547432098.3121666822248416.16611912431892.820818826
2248558.53267384431788.0605238412248680.75301799 431706.13260084
#Sta/Elev= 30
       0 2296.53    11.2 2296.38    13.6 2295.39    27.2 2286.38    41.4  2280.9
      50 2279.45    66.4  2278.8   158.1 2277.26   188.3 2278.64   244.9 2276.58
   283.4 2276.69   322.3 2278.08   378.5 2276.27   400.1  2276.7   417.4 2275.34
   469.3 2276.75   487.2  2275.6   608.3 2276.29   632.1 2274.71   665.5 2274.56
   670.3 2273.48   676.8 2272.01   682.7 2271.96   691.2 2273.43   697.3 2277.51
   701.7 2278.29   724.7 2277.86   827.4 2281.94   846.7 2283.49866.6154 2287.13
#Mann= 4 ,-1,0
       0    .016       0    13.6     .05       0   670.3    .045       0
   691.2     .05       0
#XS Ineff= 2 , 0
          397.18 2278.97
Permanent Ineff=
       F       F
Bank Sta=670.3,691.2
XS Rating Curve= 0 ,0
Exp/Cntr(USF)=0,0
Exp/Cntr=0.3,0.1

Type RM Length L Ch R = 1 ,6183    ,270.9,268,251.3
XS GIS Cut Line= 4
2248189.21132583432365.8637331582248354.50627176432240.277670517
2248457.17698009432209.7670553972248740.19146277432050.103625801
#Sta/Elev= 30
       0  2277.8    45.4 2275.09   124.3 2272.22   153.9 2272.82   189.6 2271.94
   213.5 2272.49   217.7 2272.03   224.3 2268.06   230.2 2266.22   234.4 2265.99
   251.1 2268.02   263.6 2269.47   284.4 2266.53   292.8 2266.68   301.1  2267.7
   309.5 2271.76   313.7 2272.15   329.1 2271.74   350.3 2270.26   390.7  2271.2
   400.8 2270.62   419.2 2271.55   440.7 2269.85   460.5 2271.81   501.8 2270.62
     534 2272.21   558.1 2271.69   593.3 2272.09   622.7 2274.84639.6454 2275.24
#Mann= 3 ,-1,0
       0     .04       0   224.3    .045       0   251.1     .05       0
#XS Ineff= 2 , 0
                          314.31         2272.74
Permanent Ineff=
       F       F
Bank Sta=224.3,251.1
XS Rating Curve= 0 ,0
Exp/Cntr(USF)=0,0
Exp/Cntr=0.3,0.1

Type RM Length L Ch R = 1 ,5915    ,259.8,268.4,262.1
XS GIS Cut Line= 3
2248316.94215551432624.3722980242248698.32047707432313.948082804
2248851.51684302432145.432080256
#Sta/Elev= 30
       0 2287.03     9.3 2280.53    15.9 2276.72    19.6 2275.51      33 2273.59
    62.1 2273.29   127.9 2271.09   169.8 2270.92   201.5    2268   210.5 2268.58
     232  2265.9   246.6 2266.19   266.1 2265.14   282.7 2265.47   286.1 2264.96
   291.7 2264.26     306 2264.01   311.6 2265.01   317.3 2267.11     323 2267.86
   365.7 2267.42   447.7 2268.08   496.4  2269.6   521.9 2268.25   538.9 2268.13
   565.9 2270.35   618.2 2270.94   649.6 2272.35   684.8 2272.83719.4872 2274.64
#Mann= 3 ,-1,0
       0     .04       0   286.1    .045       0   311.6     .05       0
#XS Ineff= 2 , 0
          208.68 2271.16  394.37         2270.89
Permanent Ineff=
       F       F
#Block Obstruct= 1 ,-1
   90.35   128.7 2292.04
Bank Sta=286.1,311.6
XS Rating Curve= 0 ,0
Exp/Cntr(USF)=0,0
Exp/Cntr=0.3,0.1

Type RM Length L Ch R = 1 ,5647    ,234,227.1,221.5
XS GIS Cut Line= 4
2248461.08112229432815.1107324872248623.70309623432704.083682004
2248754.32315562432608.7310386492248905.84242451432406.269946592
#Sta/Elev= 30
       0 2283.65     8.6 2282.78    23.8 2279.86    32.4 2279.03    90.9 2275.36
   141.8 2273.14   161.9 2271.17   197.5  2269.1   222.2 2266.29   230.8 2263.12
   236.5 2262.64   249.3 2263.09   256.9 2262.86   276.6  2263.5   283.2  2263.2
   293.8 2264.27   308.1 2264.88   336.2 2264.64     351 2265.78   378.1  2266.7
     448 2267.05   456.8 2267.68     468 2269.26   476.8 2268.29   488.6 2269.11
   499.7 2268.56   522.5 2270.22   531.1  2270.1   602.9 2272.12611.5101 2272.03
#Mann= 3 ,-1,0
       0     .04       0   230.8    .045       0   249.3     .05       0
#XS Ineff= 2 , 0
                           331.4         2269.37
Permanent Ineff=
       F       F
#Block Obstruct= 2 ,-1
   94.48  127.56 2295.18  133.05   176.1 2293.55
Bank Sta=230.8,249.3
XS Rating Curve= 0 ,0
Exp/Cntr(USF)=0,0
Exp/Cntr=0.3,0.1

Type RM Length L Ch R = 1 ,5420    ,301.9,343,328
XS GIS Cut Line= 4
2248505.23303166433083.6594825762248899.42251131432772.787324765
2248919.13198529432669.7605289492248996.17811086432572.109044219
#Sta/Elev= 30
       0 2362.48    75.1 2314.06      95 2302.35   112.1 2290.83   115.8 2287.72
     126 2276.89   129.2 2274.21   131.1 2273.28   152.6 2273.83   156.6 2273.15
   160.5 2271.52   166.8 2270.24   197.3 2268.42   217.7 2264.52   278.8 2263.49
   294.1 2261.87   307.6 2261.31   345.1 2260.97   360.3 2262.32   372.2 2261.07
   382.7 2259.39     396 2259.16   406.2 2261.75   411.1 2262.87   442.5 2262.53
   509.2 2264.82     566 2264.03   636.6  2264.7   676.4 2267.04   731.3 2269.19
#Mann= 5 ,-1,0
       0      .1       0     126    .016       0   160.5     .04       0
   372.2    .045       0   406.2     .05       0
#XS Ineff= 2 , 0
          323.61 2271.31  442.59         2270.25
Permanent Ineff=
       F       F
#Block Obstruct= 2 ,-1
  210.12  246.84 2285.65   262.7     317  2283.5
Bank Sta=372.2,406.2
XS Rating Curve= 0 ,0
Exp/Cntr(USF)=0,0
Exp/Cntr=0.3,0.1