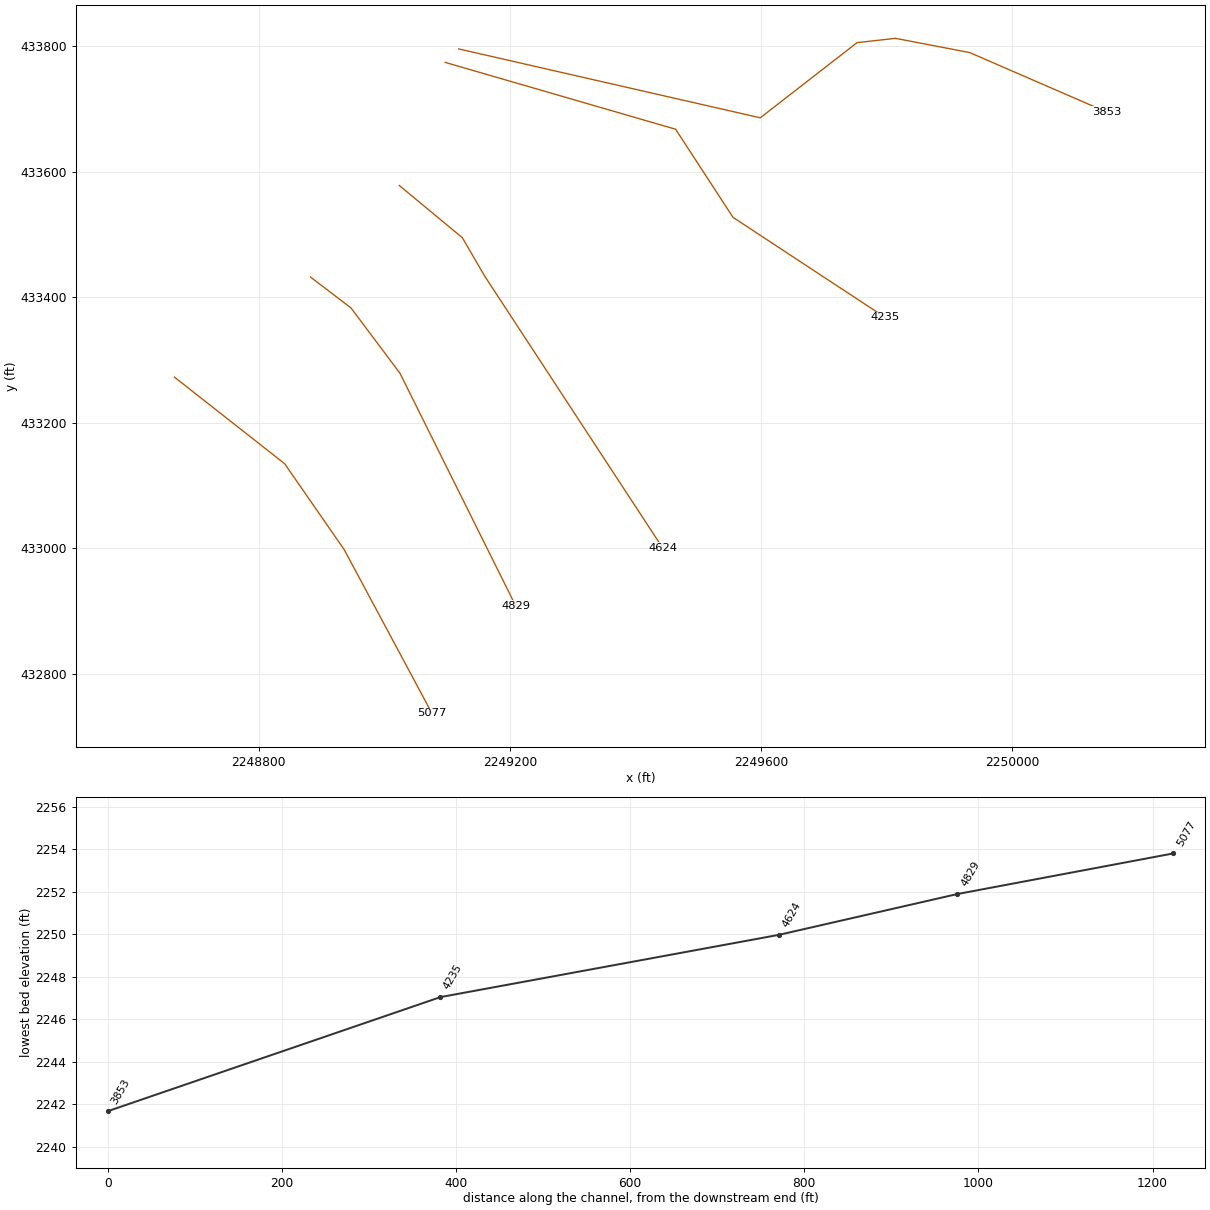
HEC-RAS study CMMNGSCK.prj: CMMNGSCK

--- CMMNGSCK.g01 (geometry) --- (continued)

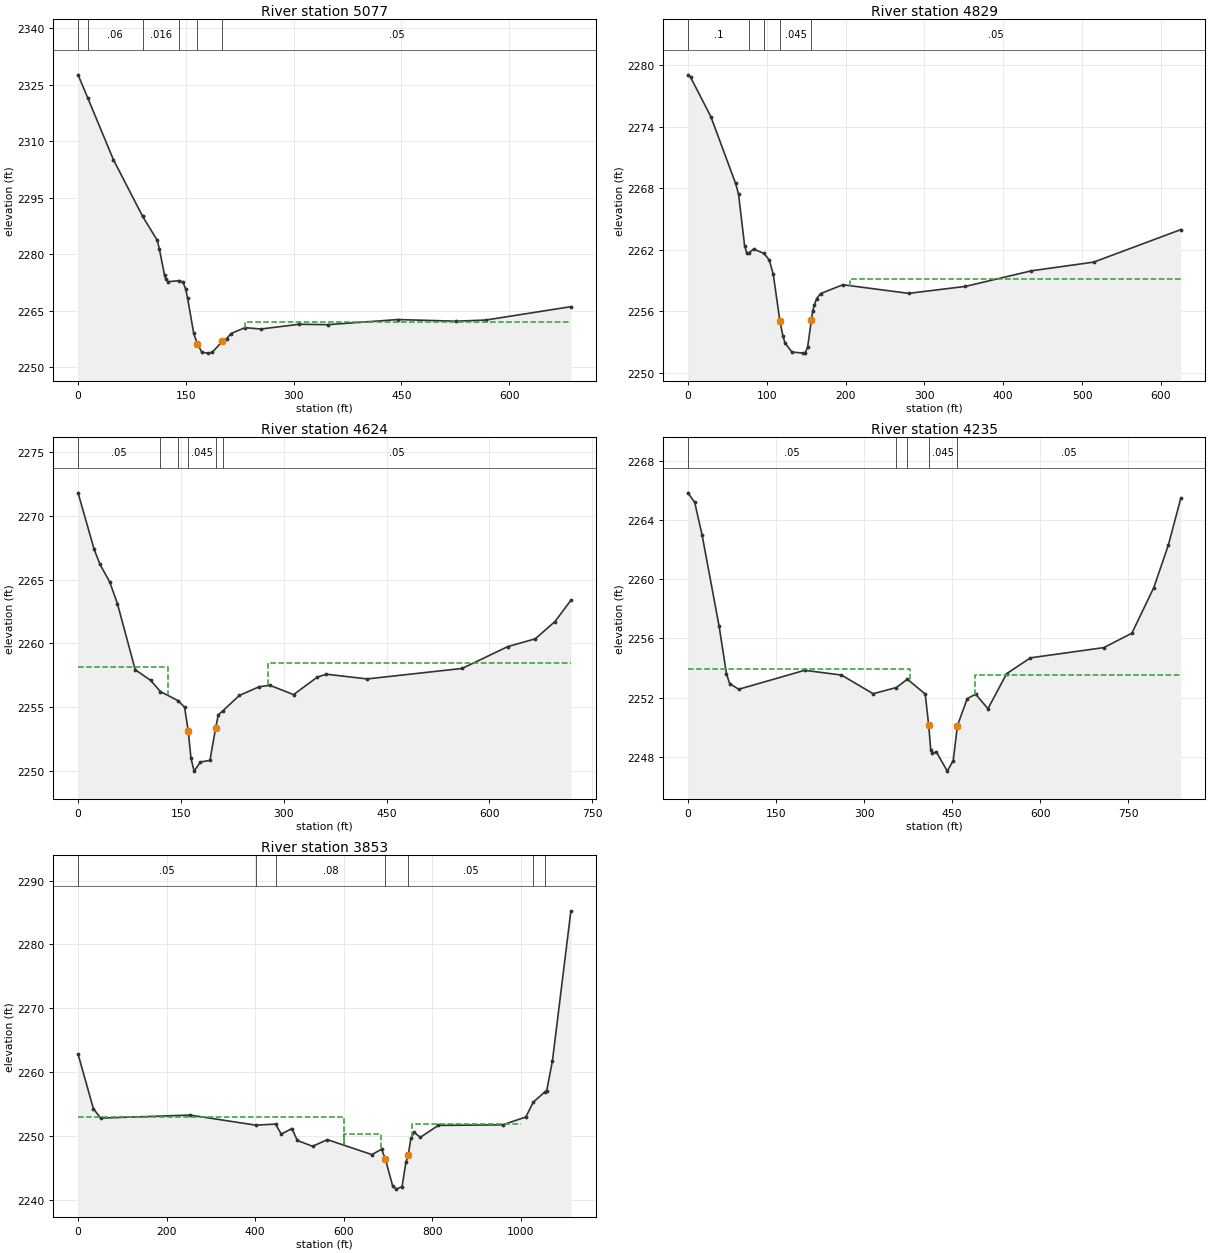
Type RM Length L Ch R = 1 ,5077    ,253.4,248,243.6
XS GIS Cut Line= 4
2248665.59647906433272.6912557692248841.18997454433134.724937893
2248936.15380373432997.6545051992249075.91189197432736.951917525
#Sta/Elev= 30
       0 2327.66    13.5 2321.53    49.1 2305.18    89.8 2290.14    89.8 2290.12
   110.1 2283.78   113.2 2281.42   120.3 2274.51   122.2 2273.38   125.4 2272.76
   141.1 2273.05   145.7 2272.71   149.6 2270.95   152.5 2268.34     161 2259.03
   166.1 2256.27   172.4 2254.02   181.3 2253.81   186.7 2254.01   200.9 2256.97
   206.8 2257.66   212.9 2259.01   232.3 2260.57   254.4 2260.21   307.9 2261.47
   347.3 2261.36   445.1 2262.72   526.3 2262.28   567.6 2262.59   685.9 2266.14
#Mann= 6 ,-1,0
       0      .1       0    13.5     .06       0    89.8    .016       0
   141.1     .08       0   166.1    .045       0   200.9     .05       0
#XS Ineff= 2 , 0
                         231.902         2261.96
Permanent Ineff=
       F       F
Bank Sta=166.1,200.9
XS Rating Curve= 0 ,0
Exp/Cntr(USF)=0,0
Exp/Cntr=0.3,0.1

Type RM Length L Ch R = 1 ,4829    ,206.9,204.9,202.2
XS GIS Cut Line= 4
2248882.40069287433432.158817988 2248946.9044259433382.885133033
2249024.84643665433278.9624520362249209.39878394432908.065987098
#Sta/Elev= 30
       0 2279.05     3.4 2278.81    29.1 2274.97    60.5 2268.45    64.2 2267.43
    71.9 2262.39    74.7 2261.65    77.4 2261.67    83.3 2262.06    96.6 2261.62
   103.3 2260.97   108.3 2259.58   116.6 2255.08   120.4 2253.61   123.3 2252.87
   131.9 2252.01   146.2  2251.9     149 2251.95   151.9  2252.5   156.6 2255.09
   158.3 2256.02   160.4 2256.61   163.3 2257.22   168.3 2257.71   196.6 2258.57
   280.1 2257.73   352.1 2258.41   435.7 2259.93   514.9 2260.78   625.3 2263.95
#Mann= 5 ,-1,0
       0      .1       0    77.4    .016       0    96.6     .08       0
   116.6    .045       0   156.6     .05       0
#XS Ineff= 1 ,-1
 205.844 625.251 2259.12
Permanent Ineff=
       F
Bank Sta=116.6,156.6
XS Rating Curve= 0 ,0
Exp/Cntr(USF)=0,0
Exp/Cntr=0.3,0.1

Type RM Length L Ch R = 1 ,4624    ,383,388.9,386
XS GIS Cut Line= 4
2249023.89472271433577.9771763122249124.28969174433494.870780659
2249159.68809736433433.9769214612249443.53112455433000.429469942
#Sta/Elev= 30
       0  2271.8    23.5 2267.36      32 2266.19    46.2 2264.81    57.5  2263.1
    83.4 2257.93   105.9  2257.1   120.1 2256.22     146  2255.5   155.4 2254.99
   160.7 2253.15   164.7    2251   169.3 2249.98   178.6  2250.7   192.4 2250.82
   200.8  2253.4   204.6 2254.39   211.3 2254.71   235.2 2255.91   263.9 2256.59
   279.7 2256.71   314.4 2255.98     349 2257.35   362.3 2257.58   421.6 2257.21
   560.3 2258.03   627.2 2259.75   666.9 2260.35   695.8 2261.71     719 2263.38
#Mann= 6 ,-1,0
       0     .05       0   120.1    .016       0     146     .08       0
   160.7    .045       0   200.8     .05       0   211.3     .05       0
#XS Ineff= 2 , 0
          131.15 2258.12 277.644         2258.42
Permanent Ineff=
       F       F
Bank Sta=160.7,200.8
XS Rating Curve= 0 ,0
Exp/Cntr(USF)=0,0
Exp/Cntr=0.3,0.1

Type RM Length L Ch R = 1 ,4235    ,327.3,382.2,393.6
XS GIS Cut Line= 4
2249097.05959249433774.1643896382249464.10195938433667.709041234
2249555.53600095433527.2924773892249797.83621112433367.936004932
#Sta/Elev= 30
       0 2265.82    11.6 2265.17    24.1 2262.98    53.2 2256.81    65.7 2253.61
    71.1 2252.96    86.5 2252.57     199 2253.85   261.6 2253.53   315.6 2252.27
   355.2 2252.69   373.9 2253.25   404.3 2252.25   410.1 2250.19   413.8 2248.47
   415.8 2248.27   423.4 2248.34   441.9 2247.05     452 2247.76   459.2 2250.12
   475.9 2251.94   490.2 2252.24   511.2 2251.26     543 2253.62   583.5 2254.69
   708.5 2255.38   756.4 2256.35   793.8 2259.43   818.6  2262.3839.7372 2265.45
#Mann= 5 ,-1,0
       0     .05       0   355.2    .016       0   373.9     .08       0
   410.1    .045       0   459.2     .05       0
#XS Ineff= 2 , 0
          379.15 2253.95  489.01         2253.54
Permanent Ineff=
       F       F
Bank Sta=410.1,459.2
XS Rating Curve= 0 ,0
Exp/Cntr(USF)=0,0
Exp/Cntr=0.5,0.3

Type RM Length L Ch R = 1 ,3853    ,77.3,61.3,57.3
BEGIN DESCRIPTION:
Channel burned based on survey CUM022BU
END DESCRIPTION:
XS GIS Cut Line= 6
2249118.57972173 433795.625310282249598.95134106433685.901721633
2249753.19393218433805.6744543552249814.46930418433812.530440033
2249932.73505711433789.8199874762250150.84110147433695.121685308
#Sta/Elev= 30
       0 2262.84    34.6 2254.28    51.1  2252.8     253 2253.28   401.4  2251.7
     446 2251.87     459  2250.3     483 2251.17   495.1 2249.31   529.6 2248.39
   563.2 2249.43   663.7 2247.09   685.5 2247.93     694 2246.41  710.91  2242.1
     719 2241.68  731.84 2242.09  740.59 2245.93  745.68 2246.99   751.7 2249.62
   759.1 2250.57     773 2249.79   813.5 2251.66   959.2 2251.75  1011.4 2252.98
  1028.1  2255.3  1053.5 2256.86  1058.4 2257.05  1071.4 2261.771113.142 2285.27
#Mann= 7 ,-1,0
       0     .05       0   401.4    .016       0     446     .08       0
     694    .045       0  745.68     .05       0  1028.1    .016       0
  1053.5      .1       0
#XS Ineff= 3 ,-1
       0     600    2253     600     685 2250.35     754    1000 2251.83
Permanent Ineff=
       F       F       F
Bank Sta=694,745.68
XS Rating Curve= 0 ,0
Exp/Cntr(USF)=0,0
Exp/Cntr=0.5,0.3