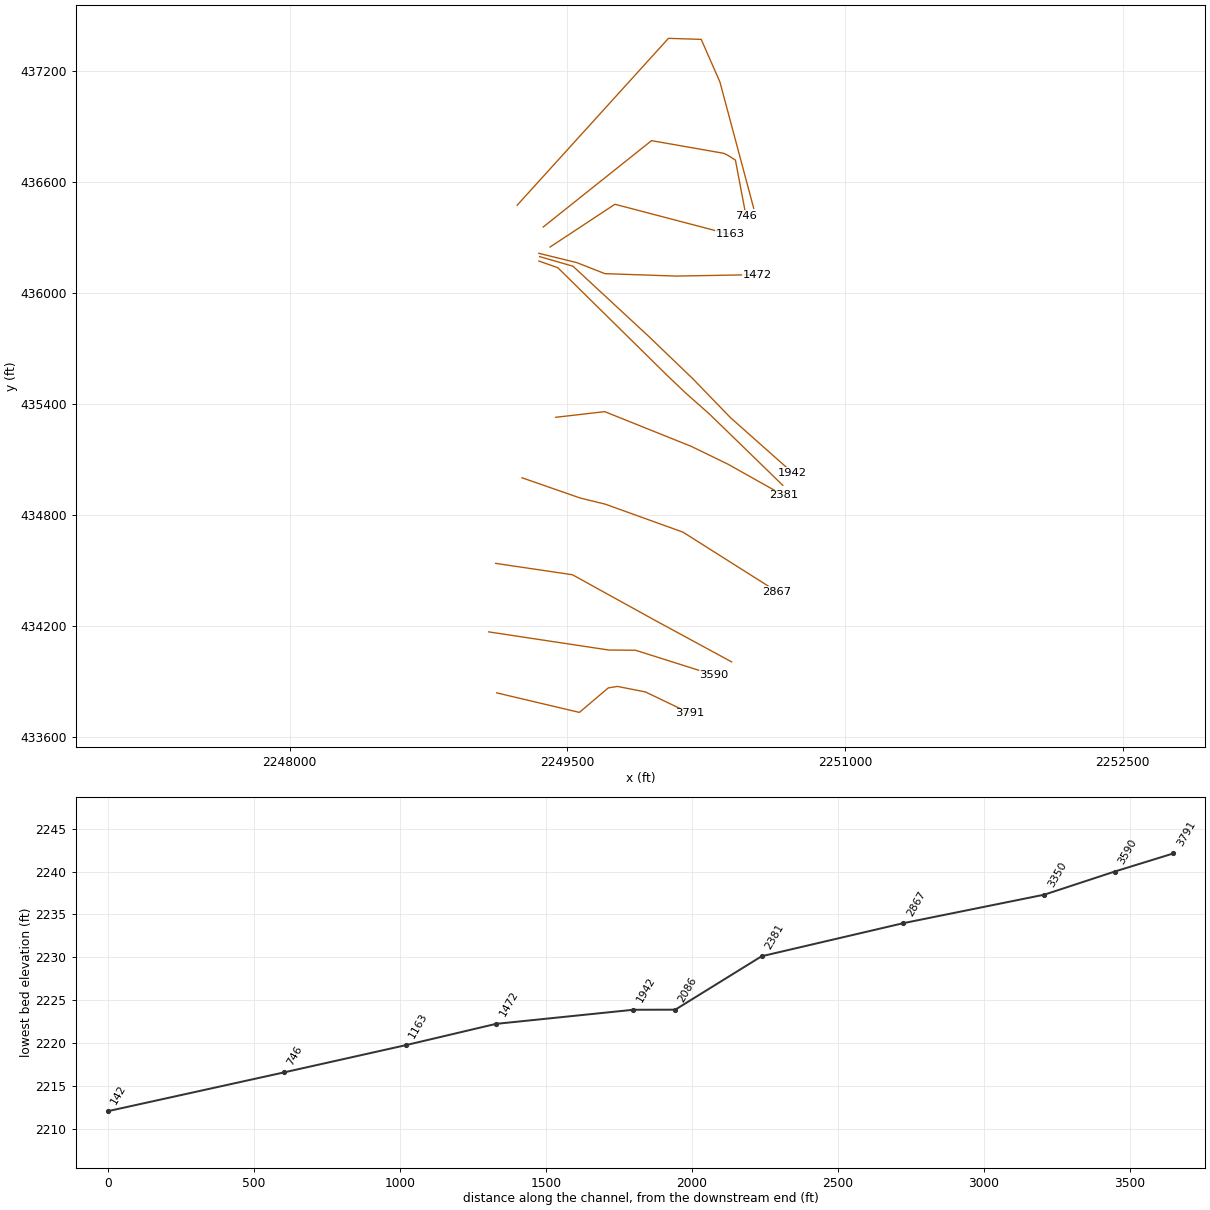
HEC-RAS study CMMNGSCK.prj: CMMNGSCK

--- CMMNGSCK.g01 (geometry) --- (continued)

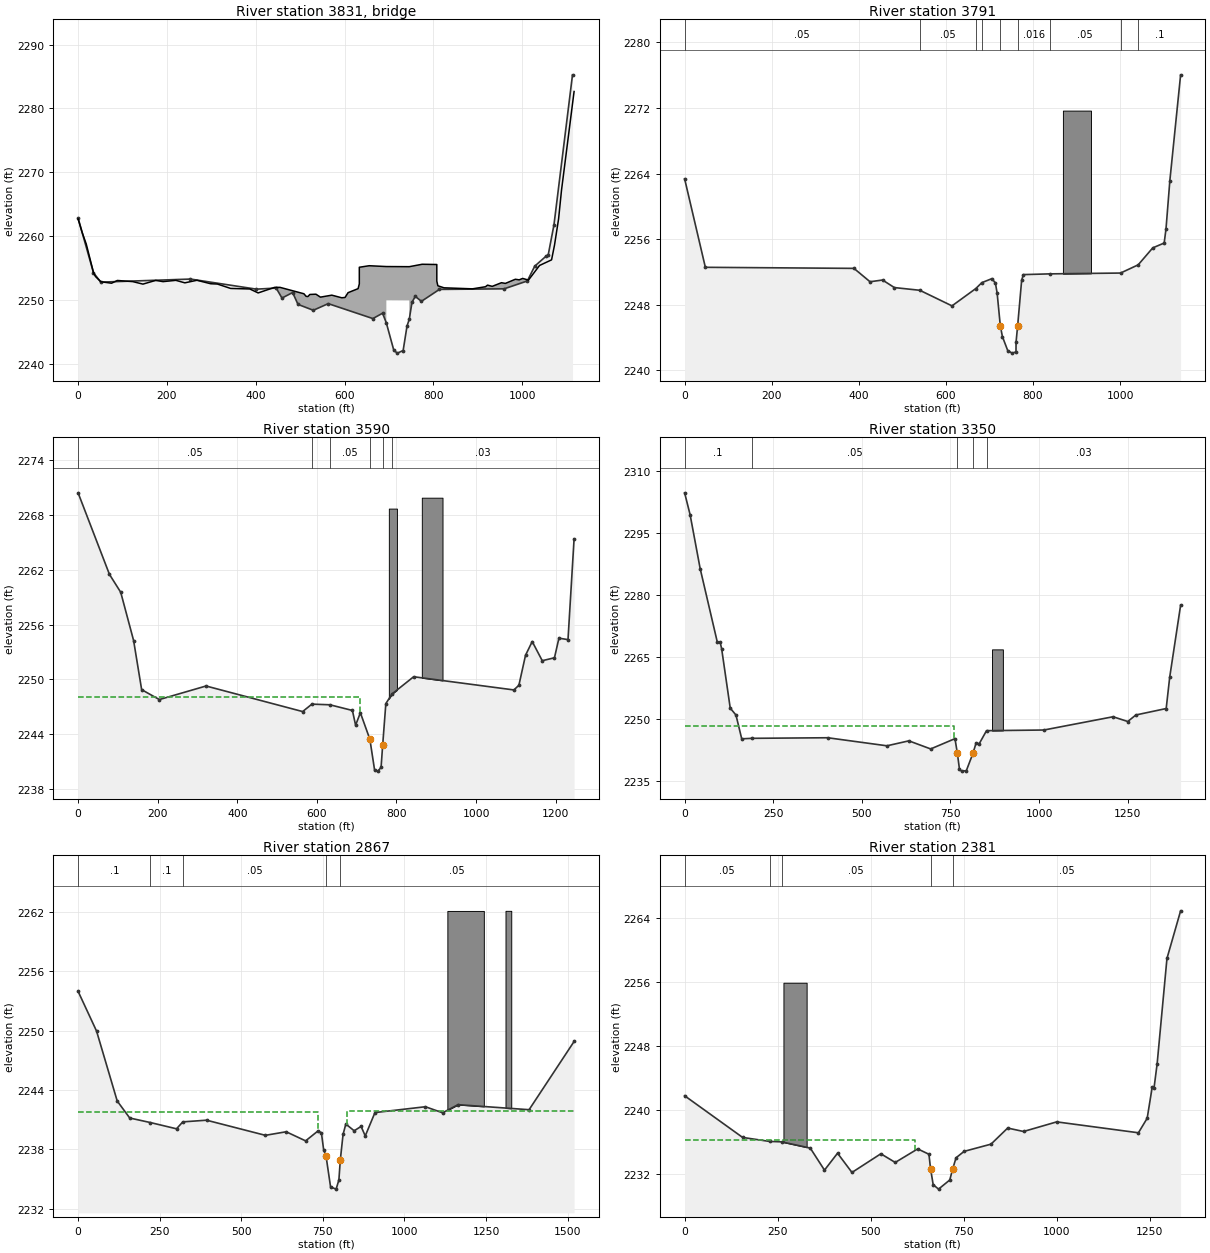
Type RM Length L Ch R = 3 ,3831    ,,,
BEGIN DESCRIPTION:
Beaver Creek Road
Survey ID: 54075CUM020
Included 2.6ft railing
END DESCRIPTION:
Bridge Culvert--1,0,-1,-1, 0
Deck Dist Width WeirC Skew NumUp NumDn MinLoCord MaxHiCord MaxSubmerge Is_Ogee
9,24,2.6,0, 60, 60, , , 0.98, 0, 0,0,,
       0     9.1    18.4    34.8      39    51.3    75.3    88.4   123.2     146
   174.6   191.3   220.1   240.4   267.6   298.3   313.7   343.5   386.5   405.4
   442.4   454.7   508.4   513.3   517.3   521.8   535.5   545.6   571.2   593.6
     601   607.8   630.4  633.16  633.16  655.39   693.9  694.06  745.68  774.65
  807.62  807.62     810   823.9     888   917.2   921.8   932.4   953.2     962
   984.4   993.1    1001    1014  1038.9    1066  1072.6  1081.8  1088.4  1116.7
 2262.69 2260.59 2258.76 2254.27 2253.69 2252.86 2252.63 2253.06 2252.88 2252.49
 2253.07 2252.88 2253.08 2252.69 2253.09 2252.55  2252.5 2251.81 2251.73 2251.11
 2251.98 2251.98 2250.98 2250.58 2250.54 2250.87 2250.91 2250.45 2250.76 2250.35
  2250.4 2251.15 2251.78 2252.53 2255.13 2255.37 2255.24 2255.24 2255.22  2255.6
 2255.56 2252.96 2252.23 2251.91 2251.75 2252.08 2252.33 2252.14 2252.71  2252.6
 2253.25 2253.16 2253.38 2253.12 2255.41 2256.29 2258.59  2262.7 2267.21 2282.66
                                                                                
                                                                                
                                                                                
                                                         2249.98 2249.96
                                                                                
                                                                                
       0     9.1    18.4    34.8      39    51.3    75.3    88.4   123.2     146
   174.6   191.3   220.1   240.4   267.6   298.3   313.7   343.5   368.3   386.5
   405.4   442.4   454.7   508.4   513.3   517.3   521.8   529.7   535.5   545.6
   571.2   593.6     601   607.8   619.1   652.6  654.16  654.16  676.39   717.5
  768.98  769.12  795.65  828.62  828.62   831.1     888   917.2   921.8   932.4
   950.3   953.2     962   984.4   993.1    1001    1014  1038.9  1060.3    1120
 2262.69 2260.59 2258.76 2254.27 2253.69 2252.86 2252.63 2253.06 2252.88 2252.49
 2253.07 2252.88 2253.08 2252.69 2253.09 2252.55  2252.5 2251.81 2251.91 2251.73
 2251.11 2251.98 2251.98 2250.98 2250.58 2250.54 2250.87 2250.76 2250.91 2250.45
 2250.76 2250.35  2250.4 2251.15 2251.53  2252.2 2252.53 2255.13 2255.37 2255.24
 2255.22 2255.22  2255.6 2255.56 2252.96 2251.93 2251.75 2252.08 2252.33 2252.14
  2252.5 2252.71  2252.6 2253.25 2253.16 2253.38 2253.12 2255.41 2256.04 2256.04
                                                                                
                                                                                
                                                                                
                                                                         2250.01
 2249.91
                                                                                
BR Coef=-1 ,-1 , 0 ,, 0 ,,,0.8,0,1,0,
WSPro=,,,, 1 ,,,, 0 ,,,, 0 ,,,,-1 ,-1 ,-1 , 0 , 0 , 0 , 0 , 0
BR U #Sta/Elev= 30
       0 2262.84    34.6 2254.28    51.1  2252.8     253 2253.28   401.4  2251.7
     446 2251.87     459  2250.3     483 2251.17   495.1 2249.31   529.6 2248.39
   563.2 2249.43   663.7 2247.09   685.5 2247.93     694 2246.41  710.91  2242.1
     719 2241.68  731.84 2242.09  740.59 2245.93  745.68 2246.99   751.7 2249.62
   759.1 2250.57     773 2249.79   813.5 2251.66   959.2 2251.75  1011.4 2252.98
  1028.1  2255.3  1053.5 2256.86  1058.4 2257.05  1071.4 2261.771113.142 2285.27
BR U #Mann= 7
       0     .05   401.4    .016     446     .08     694     .04  745.68     .05
  1028.1    .016  1053.5      .1
BR D #Sta/Elev= 30
       0 2263.36    47.6 2252.57   388.8 2252.44   425.7 2250.81   454.5 2251.02
   481.6  2250.1     540 2249.77   613.9 2247.87   668.6 2249.98   682.4  2250.7
   705.6 2251.19   713.6 2250.65   717.6 2249.41   724.8 2245.46   729.7 2244.12
  741.89 2242.42     752 2242.11  760.85 2242.26     761 2243.45   764.6 2245.41
   773.9 2251.02     778 2251.68   838.2 2251.77  1000.9 2251.87  1041.4 2252.87
  1074.9 2254.94  1101.1 2255.53  1105.3 2257.26  1114.1 2263.121138.836 2276.03
BR D #Mann= 9
       0     .05     540     .05   668.6    .016   682.4     .08   724.8     .04
   764.6    .016   838.2     .05  1000.9    .016  1041.4      .1
BC Design=,, 0 ,, 0 ,,,,,,
BC Use User HTab Curves=0
BC User HTab FreeFlow(D)= 0

Type RM Length L Ch R = 1 ,3791    ,197.5,201,202.5
BEGIN DESCRIPTION:
Channel burned from survey CUM018BD
END DESCRIPTION:
XS GIS Cut Line= 6
2249117.83434526433838.5525446132249564.67940511 433733.01907093
2249720.62392638433865.1777531482249769.99830883433873.406816889
2249921.64819779433843.4295132592250162.84678173433727.732443607
#Sta/Elev= 30
       0 2263.36    47.6 2252.57   388.8 2252.44   425.7 2250.81   454.5 2251.02
   481.6  2250.1     540 2249.77   613.9 2247.87   668.6 2249.98   682.4  2250.7
   705.6 2251.19   713.6 2250.65   717.6 2249.41   724.8 2245.46   729.7 2244.12
  741.89 2242.42     752 2242.11  760.85 2242.26     761 2243.45   764.6 2245.41
   773.9 2251.02     778 2251.68   838.2 2251.77  1000.9 2251.87  1041.4 2252.87
  1074.9 2254.94  1101.1 2255.53  1105.3 2257.26  1114.1 2263.121138.836 2276.03
#Mann= 9 ,-1,0
       0     .05       0     540     .05       0   668.6    .016       0
   682.4     .08       0   724.8    .045       0   764.6    .016       0
   838.2     .05       0  1000.9    .016       0  1041.4      .1       0
#XS Ineff= 3 ,-1
       0     700    2251     700     709    2249     776    1000    2251
Permanent Ineff=
       F       F       F
#Block Obstruct= 1 ,-1
  868.58     933 2271.67
Bank Sta=724.8,764.6
XS Rating Curve= 0 ,0
Exp/Cntr(USF)=0,0
Exp/Cntr=0.5,0.3

Type RM Length L Ch R = 1 ,3590    ,248.3,240.8,221.9
XS GIS Cut Line= 4
2249074.27566454434167.9995329922249722.98364503434069.954641531
2249868.03636116434068.6115608262250292.44986392433934.303490332
#Sta/Elev= 30
       0 2270.37    78.8 2261.47   107.1 2259.52   139.5 2254.25   159.7 2248.89
   204.2 2247.81   321.5 2249.29   564.2  2246.5   587.5 2247.31   632.7 2247.24
   689.3 2246.62   697.3 2245.01   709.3 2246.37   733.2 2243.47   745.2 2240.07
   753.1    2240   761.3  2240.4   765.3 2242.82   773.3 2247.37   788.8 2248.42
   843.2  2250.3    1095 2248.86  1107.6 2249.37  1124.3 2252.65  1141.1 2254.14
  1166.3 2252.05    1197 2252.37  1208.2 2254.51    1231 2254.351246.292 2265.35
#Mann= 6 ,-1,0
       0     .05       0   587.5    .016       0   632.7     .05       0
   733.2    .045       0   765.3     .05       0   788.8     .03       0
#XS Ineff= 2 , 0
          708.28 2248.09
Permanent Ineff=
       F       F
#Block Obstruct= 2 ,-1
   780.8  801.13 2268.65  863.66  915.69 2269.84
Bank Sta=733.2,765.3
XS Rating Curve= 0 ,0
Exp/Cntr(USF)=0,0
Exp/Cntr=0.3,0.1

Type RM Length L Ch R = 1 ,3350    ,477.5,482.9,486.7
XS GIS Cut Line= 4
2249112.84642648434537.8883097052249526.99986801434476.608992456
2249970.34430285 434231.80058299 2250387.2144103434005.770957412
#Sta/Elev= 30
       0 2304.67    15.5 2299.37    43.8 2286.35    92.3 2268.51   100.4 2268.45
   104.5  2266.9   128.7 2252.56   144.9 2250.88   161.1 2245.13   189.4 2245.25
   403.7 2245.39   570.8 2243.44   632.6 2244.64   694.2 2242.68   762.7 2245.17
   769.4 2241.68   775.3 2237.84   781.2 2237.31   794.7 2237.41   813.6 2241.64
   822.1 2244.08   831.3 2243.97   851.7  2247.1  1013.6 2247.26  1208.7 2250.47
  1250.2 2249.32    1273  2250.9  1358.6 2252.46  1368.6  2260.1  1399.3 2277.47
#Mann= 5 ,-1,0
       0      .1       0   189.4     .05       0   769.4    .045       0
   813.6     .05       0   851.7     .03       0
#XS Ineff= 2 , 0
          761.13 2248.19
Permanent Ineff=
       F       F
#Block Obstruct= 1 ,-1
  867.21  897.87 2266.78
Bank Sta=769.4,813.6
XS Rating Curve= 0 ,0
Exp/Cntr(USF)=0,0
Exp/Cntr=0.3,0.1

Type RM Length L Ch R = 1 ,2867    ,477.2,485.2,478.4
XS GIS Cut Line= 5
2249254.70882717435000.3497265572249568.39465488434891.130473097
2249705.25751231434857.5699937382250124.24719121  434706.6206678
2250632.71867056434385.037556021
#Sta/Elev= 30
       0 2253.99    56.6 2249.97   119.9  2242.9   158.3 2241.18   221.8 2240.72
   301.6 2240.09   320.9 2240.79   393.7 2240.96     574 2239.43   637.7 2239.79
   697.3 2238.87   735.5 2239.88   745.7 2239.68   752.5 2237.99   760.1 2237.29
   773.8 2234.21   790.8 2233.99   799.3 2234.92   803.6 2236.93   812.1 2239.53
   820.6 2240.57   846.1 2239.89   867.3 2240.33   880.1 2239.37   909.8 2241.73
  1064.4 2242.32  1117.1 2241.71  1164.4 2242.53  1382.2 2242.02  1520.1 2248.92
#Mann= 5 ,-1,0
       0      .1       0   221.8      .1       0   320.9     .05       0
   760.1    .045       0   803.6     .05       0
#XS Ineff= 2 , 0
        734.6716 2241.81823.9142         2241.84
Permanent Ineff=
       F       F
#Block Obstruct= 2 ,-1
 1131.74 1243.48 2262.12 1309.89 1327.54 2262.13
Bank Sta=760.1,803.6
XS Rating Curve= 0 ,0
Exp/Cntr(USF)=0,0
Exp/Cntr=0.3,0.1

Type RM Length L Ch R = 1 ,2381    ,334.2,295.7,288.5
XS GIS Cut Line= 5
2249437.26312157435327.0814972022249701.54924997435357.541593356
2250168.30542928435170.3015905252250367.29148226435073.745076572
2250666.61667551434905.617290936
#Sta/Elev= 30
       0 2241.79   155.9 2236.59   228.4 2236.09   260.6 2236.04   337.8 2235.26
     376 2232.51   411.1 2234.62   449.9 2232.22   527.5 2234.55   566.2 2233.47
   626.6 2235.16   656.8 2234.49   661.1 2232.71   668.2  2230.7   682.6 2230.14
   712.8 2231.28   720.5 2232.63   729.7 2234.05   751.3 2234.85   823.6 2235.75
   868.5 2237.76   911.1 2237.33  1000.3 2238.53    1220 2237.17  1243.5 2238.98
  1257.2 2242.91  1261.8 2242.71  1270.3 2245.78  1296.7 2258.92  1333.4 2264.86
#Mann= 5 ,-1,0
       0     .05       0   228.4    .016       0   260.6     .05       0
   661.1    .045       0   720.5     .05       0
#XS Ineff= 2 , 0
        619.9243 2236.33
Permanent Ineff=
       F       F
#Block Obstruct= 1 ,-1
  265.66     328 2255.89
Bank Sta=661.1,720.5
XS Rating Curve= 0 ,0
Exp/Cntr(USF)=0,0
Exp/Cntr=0.5,0.3

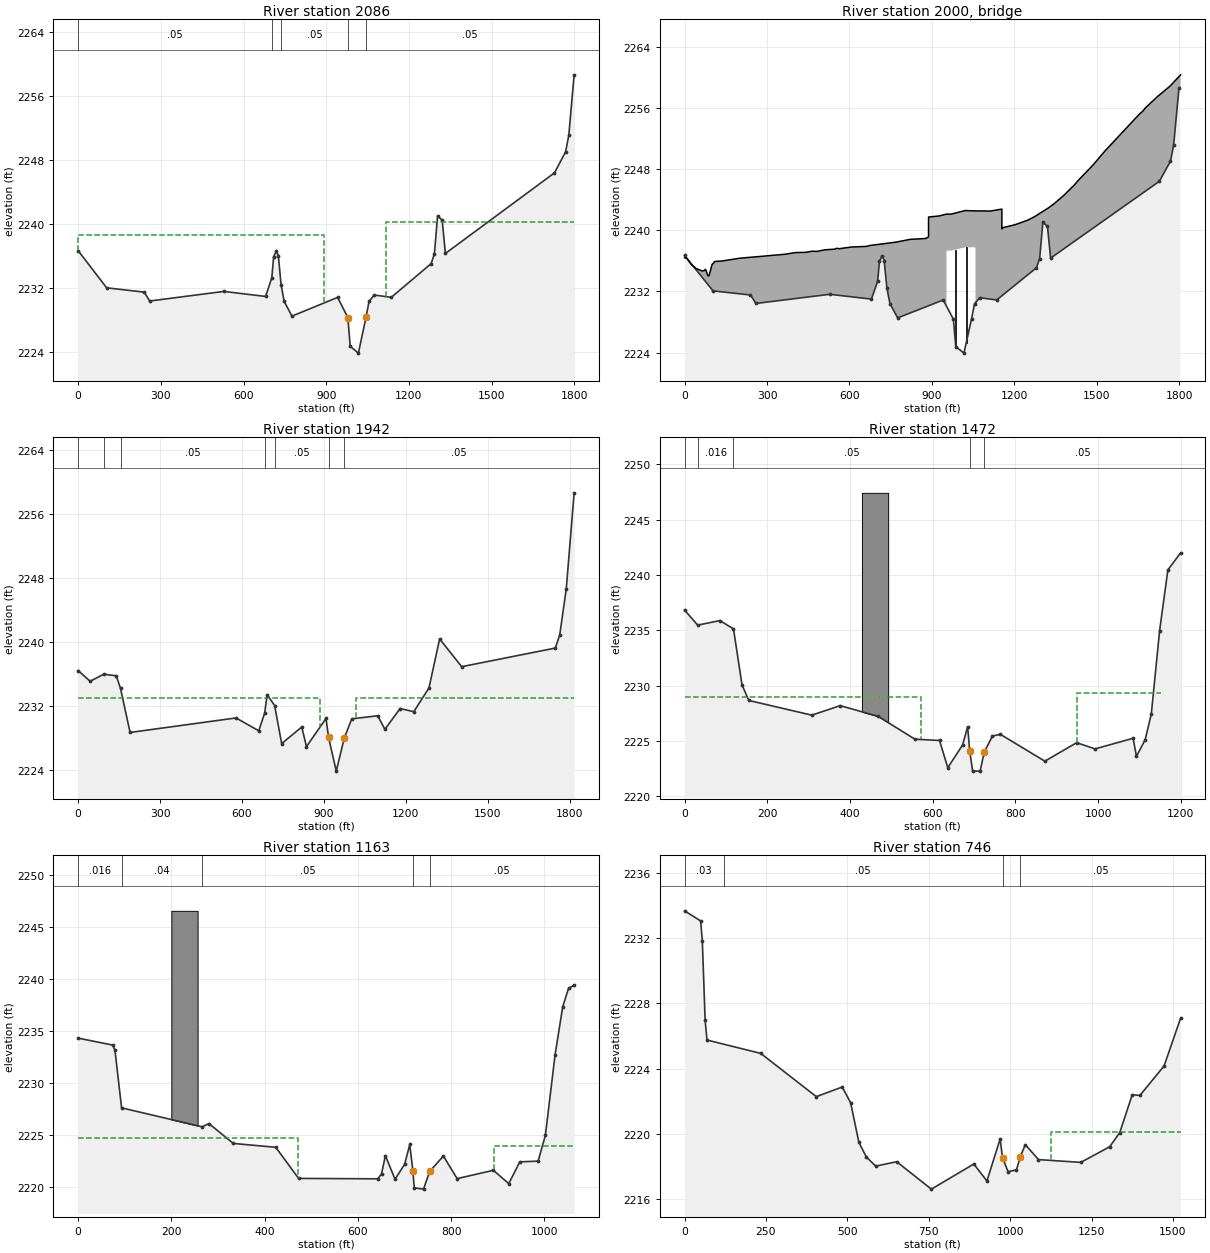
Type RM Length L Ch R = 1 ,2086    ,116,143.7,127.2
BEGIN DESCRIPTION:
Channel burned from survey CUM012BU
END DESCRIPTION:
XS GIS Cut Line= 6
2249345.88283311436171.0053377122249448.01374374436135.169930471
2250037.50619285435554.6363331782250135.15767758435461.464274353
2250267.74868437435344.1033156412250663.33176318 434959.66903019
#Sta/Elev= 30
       0 2236.73   103.6 2232.08   239.9 2231.54   259.7 2230.43   528.4 2231.63
   680.2    2231   702.6 2233.32   709.4 2235.99   719.4 2236.66   726.4 2236.06
   736.3 2232.47   747.5 2230.39   775.6 2228.54   941.4 2230.88  978.43 2228.36
  987.01 2224.78 1016.67 2223.92 1044.38  2228.4  1055.4 2230.39  1074.3 2231.18
    1136 2230.89  1280.5  2235.1  1292.4 2236.31    1304 2241.08  1320.7 2240.53
  1332.2 2236.37  1727.9 2246.44  1768.4 2249.08  1779.9 2251.14  1799.3 2258.69
#Mann= 5 ,-1,0
       0     .05       0   702.6    .016       0   736.3     .05       0
  978.43    .045       0 1044.38     .05       0
#XS Ineff= 2 , 0
        893.0215 2238.671118.027         2240.36
Permanent Ineff=
       F       F
Bank Sta=978.43,1044.38
XS Rating Curve= 0 ,0
Exp/Cntr(USF)=0,0
Exp/Cntr=0.5,0.3

Type RM Length L Ch R = 3 ,2000    ,,,
BEGIN DESCRIPTION:
Huntersville Road
Survey ID: 54075CUM010
Include 2.6 ft railing
END DESCRIPTION:
Bridge Culvert--1,0,-1,-1, 0
Deck Dist Width WeirC Skew NumUp NumDn MinLoCord MaxHiCord MaxSubmerge Is_Ogee
60,32,2.6,0, 60, 60, , , 0.98, 0, 0,0,,
       0     8.6    24.5    42.2    63.2    71.6    75.8    78.6    84.2    88.4
    94.6    96.8   100.8   104.1   109.4   136.9   200.8   365.2   403.3   440.6
   463.8   481.2   510.2   546.9   552.5   562.9   607.7     663   672.5   769.5
   820.4   877.9  887.93  887.93  926.51  953.36  970.04    1021 1058.71 1080.24
 1112.07 1154.77 1154.77  1156.2  1202.4  1248.6  1274.8  1323.9  1343.7  1379.3
  1419.8  1432.3  1485.3  1530.5    1656  1667.8    1676  1720.7  1765.5  1805.3
 2236.42 2236.34 2235.53 2235.01  2234.7 2234.73 2234.91 2234.72 2234.11 2234.03
 2234.75 2235.13  2235.6 2235.65 2235.93    2236 2236.36 2236.88  2237.1 2237.13
 2237.28 2237.25 2237.46 2237.55 2237.66 2237.61 2237.83 2237.91 2238.02 2238.47
 2238.83 2238.95 2239.16 2241.76  2241.9 2242.14 2242.14 2242.61 2242.56 2242.56
 2242.54  2242.8  2240.2 2240.35 2240.75 2241.34 2241.83 2242.95 2243.47 2244.57
 2246.01 2246.55 2248.53 2250.44 2255.28 2255.64 2256.03 2257.54 2258.88  2260.4
                                                                                
                                                                                
                                                                                
                                         2237.35 2237.35 2237.79 2237.79
                                                                                
                                                                                
       0     8.6    24.5    42.2    63.2    71.6    75.8    78.6    84.2    88.4
    94.6    96.8   100.8   104.1   109.4   136.9   200.8   365.2   403.3   440.6
   463.8   481.2   510.2   546.9   552.5   562.9   607.7     663   672.5   707.2
   713.1   718.2   724.7   800.6  811.93  811.93  894.04  899.08     940 1004.24
 1036.07 1078.77 1078.77  1081.2  1134.4  1224.4  1248.6  1298.5  1343.7  1379.3
  1419.8  1432.3  1485.3  1530.5    1656  1667.8    1676  1720.7  1765.5  1805.3
 2236.42 2236.34 2235.53 2235.01  2234.7 2234.73 2234.91 2234.72 2234.11 2234.03
 2234.75 2235.13  2235.6 2235.65 2235.93    2236 2236.36 2236.88  2237.1 2237.13
 2237.28 2237.25 2237.46 2237.55 2237.66 2237.61 2237.83 2237.91 2238.02 2238.19
 2238.15 2238.24 2238.21 2238.67 2239.16 2241.76 2242.14 2242.14 2242.61 2242.56
 2242.54  2242.8  2240.2 2239.88 2240.14 2240.99 2241.34 2242.35 2243.47 2244.57
 2246.01 2246.55 2248.53 2250.44 2255.28 2255.64 2256.03 2257.54 2258.88  2260.4
                                                                                
                                                                                
                                                                                
                                                         2237.14 2237.61 2237.62
                                                                                
                                                                                
Pier Skew, UpSta & Num, DnSta & Num=  ,987.34, 2 ,938.15, 2 , 0 , 0 , 0 ,,
     3.5     3.5
       0    2239
     3.5     3.5
       0    2239
Pier Skew, UpSta & Num, DnSta & Num=  ,1024.68, 2 ,975.46, 2 , 0 , 0 , 0 ,,
     3.5     3.5
       0    2239
     3.5     3.5
       0    2239
BR Coef=-1 ,-1 , 0 ,0.9, 0 ,,,0.8,0,1.33,0,
WSPro=,,,, 1 ,,,, 0 ,,,, 0 ,,,,-1 ,-1 ,-1 , 0 , 0 , 0 , 0 , 0
BC Design=,, 0 ,, 0 ,,,,,,
BC Use User HTab Curves=0
BC User HTab FreeFlow(D)= 0

Type RM Length L Ch R = 1 ,1942    ,449.2,469.8,499.5
BEGIN DESCRIPTION:
Channel burned from survey CUM008BD
END DESCRIPTION:
XS GIS Cut Line= 6
2249349.76691389436194.9409428252249530.00901706436143.053064638
2249936.91921968435766.1832125452250177.24202392435535.418701662
2250380.69712523435325.1362479582250715.69127487435027.855846745
#Sta/Elev= 30
       0 2236.45    44.1 2235.11    93.9 2235.99   139.9 2235.79   155.3 2234.21
   190.3 2228.73   578.2 2230.54   661.3 2228.94   682.9 2231.14   692.1 2233.44
   719.4 2232.09   745.2 2227.34   818.7 2229.41     836 2226.97   907.5 2230.48
  916.89 2228.11     945 2223.91  974.24 2228.02  1001.8 2230.43  1096.8 2230.81
    1123 2229.12  1178.7 2231.71  1228.8 2231.32  1284.4 2234.28  1323.4 2240.39
  1404.1 2236.93    1747 2239.25    1763 2240.89  1786.9 2246.62  1815.8  2258.6
#Mann= 7 ,-1,0
       0     .05       0    93.9    .016       0   155.3     .05       0
   682.9    .016       0   719.4     .05       0  916.89    .045       0
  974.24     .05       0
#XS Ineff= 2 ,-1
       0 886.981    22331015.978 1815.76    2233
Permanent Ineff=
       F       F
Bank Sta=916.89,974.24
XS Rating Curve= 0 ,0
Exp/Cntr(USF)=0,0
Exp/Cntr=0.5,0.3

Type RM Length L Ch R = 1 ,1472    ,325.3,309.2,273.4
XS GIS Cut Line= 5
2249345.30283996 436212.919793122249549.65203768436162.829636015
2249702.55840228436102.9233424052250088.28917738 436089.83158423
2250526.94920536436097.669951571
#Sta/Elev= 30
       0 2236.83    31.8 2235.47    85.3 2235.88   118.3 2235.13   138.9 2230.07
   155.3 2228.66   307.6 2227.33   376.2 2228.19   468.3 2227.22   556.8 2225.16
   616.4 2225.04   636.4 2222.58   672.1 2224.63   684.4 2226.28   689.4 2224.11
   696.4 2222.28   714.6 2222.27   724.4 2223.98   744.5 2225.45   763.8 2225.59
   871.1 2223.17   947.9 2224.84   992.5 2224.28  1084.5 2225.24  1092.5  2223.6
  1113.6 2225.11  1128.5 2227.45  1148.5 2234.97  1168.5 2240.46  1199.3    2242
#Mann= 5 ,-1,0
       0     .05       0    31.8    .016       0   118.3     .05       0
   689.4    .045       0   724.4     .05       0
#XS Ineff= 2 ,-1
       0  571.832228.927  949.99 1151.222229.327
Permanent Ineff=
       F       F
#Block Obstruct= 1 ,-1
  428.81  492.27 2247.43
Bank Sta=689.4,724.4
XS Rating Curve= 0 ,0
Exp/Cntr(USF)=0,0
Exp/Cntr=0.3,0.1

Type RM Length L Ch R = 1 ,1163    ,393.3,416.9,412.4
XS GIS Cut Line= 3
2249406.24550382436246.7782986042249756.63615239436477.717589708
2250379.77406718436314.467401169
#Sta/Elev= 30
       0  2234.3    74.2 2233.63      79 2233.15    93.3  2227.6     266 2225.78
   280.6 2226.09   332.9 2224.18   423.9 2223.81   472.9 2220.82   642.7 2220.78
   650.7 2221.25     659 2223.01   679.7 2220.74   700.4 2222.19   711.3 2224.08
   717.9 2221.56     721 2219.91   740.8 2219.79   754.1  2221.5   783.4 2222.97
   812.9  2220.8   890.6  2221.6   923.6 2220.32   947.2 2222.41   986.6 2222.48
  1002.2 2224.98  1022.9 2232.69  1039.4 2237.33  1051.8 2239.081063.818 2239.39
#Mann= 5 ,-1,0
       0    .016       0    93.3     .04       0     266     .05       0
   717.9    .045       0   754.1     .05       0
#XS Ineff= 2 , 0
          472.43 2224.73  891.04         2223.95
Permanent Ineff=
       F       F
#Block Obstruct= 1 ,-1
  199.99  256.28 2246.53
Bank Sta=717.9,754.1
XS Rating Curve= 0 ,0
Exp/Cntr(USF)=0,0
Exp/Cntr=0.3,0.1

Type RM Length L Ch R = 1 ,746     ,580.4,603.7,611.9
XS GIS Cut Line= 6
 2249369.4830166436355.0892076072249954.36574302436821.468088213
2250343.76900297436753.0594074112250366.92438265436742.190917396
2250407.43721683436716.3882380362250464.64197013 436415.27540869
#Sta/Elev= 30
       0 2233.68    49.5 2233.06    54.6 2231.81    63.2 2226.97    68.9 2225.76
     234 2224.94   404.7 2222.29   484.3 2222.88   510.1 2221.91   535.5 2219.48
   558.4 2218.59   586.9 2218.03   651.4  2218.3     758 2216.62   888.4 2218.16
   928.6 2217.12   969.2 2219.69   976.6 2218.54   993.6 2217.69  1019.3  2217.8
  1030.8 2218.58  1046.4 2219.35    1087 2218.43    1217 2218.26  1305.8 2219.22
  1336.7 2220.09    1375 2222.41  1398.3 2222.36  1472.7 2224.17  1523.5  2227.1
#Mann= 4 ,-1,0
       0     .03       0     120     .05       0   976.6    .045       0
  1030.8     .05       0
#XS Ineff= 2 , 0
                         1124.47        2220.129
Permanent Ineff=
       F       F
Bank Sta=976.6,1030.8
XS Rating Curve= 0 ,0
Exp/Cntr(USF)=0,0
Exp/Cntr=0.3,0.1

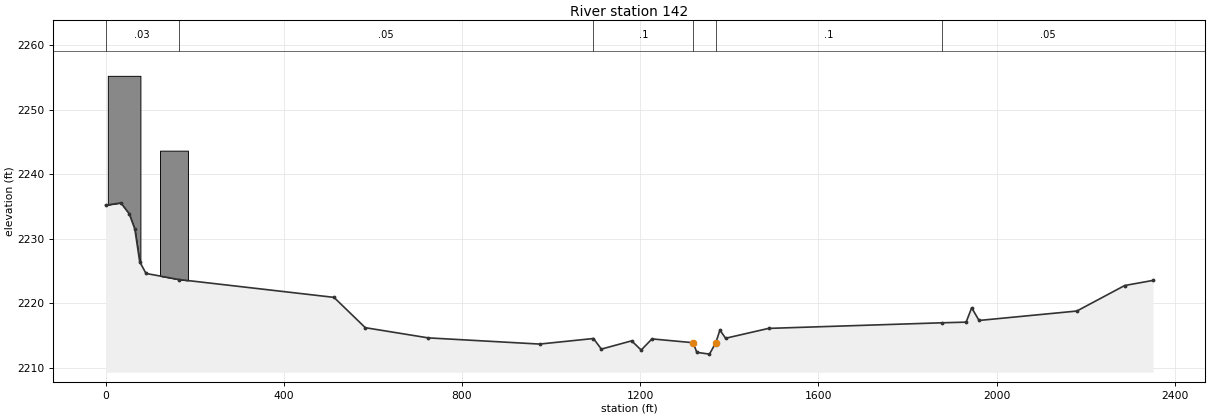
Type RM Length L Ch R = 1 ,142     ,,,
XS GIS Cut Line= 5
2249228.65227247436472.666401065 2250045.7942718 437374.04984362
2250222.70130258437368.4337474052250323.79103445437138.173802578
2250506.31416145436455.818112419
#Sta/Elev= 30
       0 2235.19      34 2235.55    52.9 2233.86    65.5 2231.48    76.5 2226.41
    90.6 2224.61   164.3 2223.67   512.6  2220.9   582.9  2216.2   724.2 2214.62
   974.2 2213.66  1095.1 2214.52  1112.9 2212.88  1180.9 2214.16  1202.3 2212.73
  1226.5 2214.46  1319.1 2213.87  1327.1 2212.38  1355.6  2212.1 1369.63 2213.85
  1379.1 2215.83  1391.8 2214.56  1488.3 2216.09    1878 2216.96  1931.8 2217.06
  1944.3 2219.28  1960.8 2217.32  2180.3 2218.78  2287.9 2222.742351.455 2223.53
#Mann= 6 ,-1,0
       0     .03       0   164.3     .05       0  1095.1      .1       0
  1319.1    .045       0 1369.63      .1       0    1878     .05       0
#Block Obstruct= 2 ,-1
    4.84   78.02 2255.25  122.08  184.71 2243.65
Bank Sta=1319.1,1369.63
XS Rating Curve= 0 ,0
Exp/Cntr(USF)=0,0
Exp/Cntr=0.3,0.1
LCMann Table=0

Chan Stop Cuts=-1
Use User Specified Reach Order=0
Composite Channel Slope=5